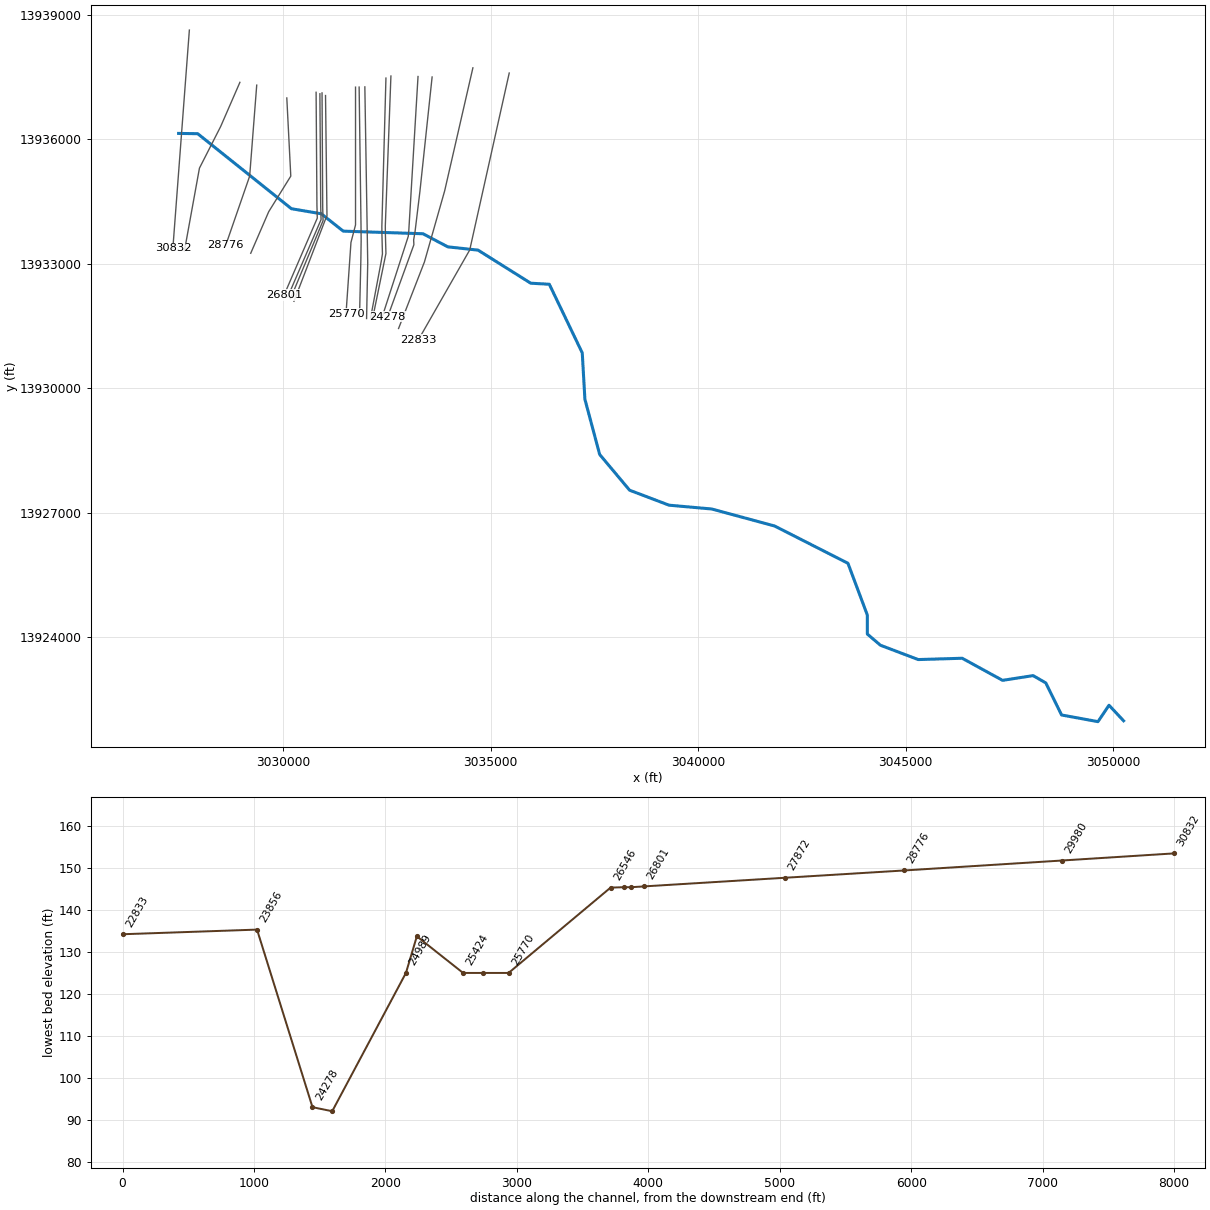
--- K142-00-00.prj (project) ---

Proj Title=K142-00-00
Current Plan=p02
Default Exp/Contr=.3,.1
English Units
Geom File=g01
Flow File=f02
Flow File=f01
Plan File=p02
Plan File=p01
Y Axis Title=Elevation
X Axis Title(PF)=Main Channel Distance
X Axis Title(XS)=Station
BEGIN DESCRIPTION:
vc  x HCFCD MODEL SUMMARY METADATA
The purpose of this summary is to document the high points of hydrologic and hydraulic models filed within the HCFCD Model and Map Management (M3) system.  The document includes references to the project that prompted the creation or update of the model.
DESCRIPTION OF PROJECT:
The following model was the hydraulic model which represented the effective condition of Harris County's watersheds.
PURPOSE OF PROJECT:
Development of effective models to support the National Flood Insurance Program.
REVISED MODEL:
AECOM, February
Enclave at Northpointe LOMR
HCFCD Watershed Unit ID: K
M3 Study Identifier: 2007_Effective_K
Engineer: HCFCD
Project Name: EffectiveFEMA Study for watershed Cypress Creek (K)
Study Completion Date: 6/18/2007
FEMA Case Number: [No Data]
FEMA Approval Date: [No Date in Database]
Vertical Datum: NAVD 1988
Datum Note: 2001 ADJ
HYDRAULICS
HCFCD Unit No.:  K142-00-00
Hydraulic Program Name: HEC-RAS
Hydraulic Program Version: 3.0.1
Steady Hydraulic Model: Yes
Unsteady Hydraulic Model: No
Update1:
The effective FEMA hydraulic model for unit number K142-00-00 has been updated by FEMA LOMR 08-06-1092P with an effective date of 8/6/2008.
Update2:
The effective FEMA hydraulic model for unit number K142-00-00 has been updated by FEMA LOMR 15-06-1734P with an effective date of 1/22/2016.
END DESCRIPTION:
DSS File=dss
DSS Export Rating Curves= 0
DSS Export Rating Curve Sorted= 0
DSS Export Volume Flow Curves= 0
DXF Filename=..\..\..\0-Received_Packages\Original Submittal\Models\Hydraulics\HEC-RAS 3.0.1\K1420000LOMR.
DXF OffsetX= 0
DXF OffsetY= 0
DXF ScaleX= 1
DXF ScaleY= 10

--- K142-00-00.p02 (plan) ---

Plan Title=Effective Floodway 2018
Version=Version 3.0.1  May 2012
Short Identifier=Eff+LOMR FW
Geom File=g01
Flow File=f02
Subcritical Flow
K Sum by GR= 0
Std Step Tol= 0.01
Critical Tol= 0.01
Num of Std Step Trials= 20
Max Error Tol= 0.3
Flow Tol Ratio= 0.001
Split Flow NTrial= 30
Split Flow Tol= 0.02
Split Flow Ratio= 0.02
Log Output Level= 0
Friction Slope Method= 1
Unsteady Friction Slope Method= 2
Parabolic Critical Depth
Global Vel Dist= 0 , 0 , 0
Global Log Level= 0
CheckData=True
Encroach Param= 0 ,0,0, 2
Encroach River=K142-00-00
Encroach Reach=K142-00-00_0018
Encroach Node=30832
       1 4522.79 5460.82
Encroach Node=29980
       1 4474.09 5412.12
Encroach Node=28776
       1 4522.29 5517.32
Encroach Node=27872
       1 4552.95 5449.06
Encroach Node=26801
       1 4717.76 5279.65
Encroach Node=26704
       1 4717.76 5279.65
Encroach Node=26676.5
       1 4717.76 5279.65
Encroach Node=26649
       1 4717.76 5279.65
Encroach Node=26546
       1 4717.76 5279.65
Encroach Node=25770
       1  4659.5    5302
Encroach Node=25575
       1    4657    5120
Encroach Node=25424
       1    4650    5126
Encroach Node=25072
       1    4707    5183
Encroach Node=24989
       1    4715    5128
Encroach Node=24428
       1    4700    5143
Encroach Node=24278
       1    4711    5143
Encroach Node=23856
       1    4615    5097
Encroach Node=22833
       1    4675    5043
Encroach Node=22422
       1    4597    5360
Encroach Node=21735
       1    4600    5323
Encroach Node=21376
       1    4576    5358
Encroach Node=20528
       1    4903    5210
Encroach Node=20341
       1    4889 5294.75
Encroach Node=20247
       1  4563.5 5337.23
Encroach Node=19814
       1  4925.4 5425.11
Encroach Node=19718
       1 4909.75 5184.44
Encroach Node=19638
       1  4947.2    5201
Encroach Node=18877
       1  4971.5  5194.5
Encroach Node=18775
       1  4973.8 5179.02
Encroach Node=18756
       1  4973.8    5179
Encroach Node=18737
       1  4973.8    5179
Encroach Node=18636
       1 4938.52 5058.33
Encroach Node=17789
       1 4895.03  5039.9
Encroach Node=17685
       13979.4414168.501
Encroach Node=17652.5
       13979.441  4168.5
Encroach Node=17620
       13979.4414168.501
Encroach Node=17522
       1  4944.2  5057.3
Encroach Node=16692
       1  4939.2 5058.63
Encroach Node=15926
       1  4940.9  5055.5
Encroach Node=15019
       1  4917.7    5050
Encroach Node=14922
       1 4933.46 5070.96
Encroach Node=14912
       1 4933.46 5070.96
Encroach Node=14902
       1 4933.46 5070.96
Encroach Node=14802
       1  4931.3 5065.04
Encroach Node=14144
       1  4925.1  5057.9
Encroach Node=13338
       1  4902.3  5082.3
Encroach Node=12675
       1  4933.1  5083.1
Encroach Node=12578
       1  4907.5  5086.2
Encroach Node=12523
       1  4907.5  5086.2
Encroach Node=12468
       1  4907.5  5086.2
Encroach Node=12363
       1  4913.1  5063.1
Encroach Node=11266
       1  4934.6  5066.5
Encroach Node=10586
       1  4909.8  5059.8
Encroach Node=9438
       1 4929.76 5068.36
Encroach Node=9340
       1  4931.5  5069.1
Encroach Node=9331
       1  4931.5  5069.1
Encroach Node=9322
       1    4926  5067.5
Encroach Node=9228
       1  4911.5  5079.1
Encroach Node=9182
       1  4911.5  5079.1
Encroach Node=9136
       1  4911.5  5079.1
Encroach Node=9028
       1 4913.95  5082.5
Encroach Node=8142
       1  4933.4 5098.75
Encroach Node=8044
       1  4934.3  5098.4
Encroach Node=8030
       1  4934.3  5098.4
Encroach Node=8016
       1  4934.3  5098.4
Encroach Node=7911
       1  4924.5 5094.23
Encroach Node=7229
       1 4890.15 5054.25
Encroach Node=6591
       1  4910.5    5095
Encroach Node=5595
       1  4886.7  5075.6
Encroach Node=4732
       1  4884.7    5063
Encroach Node=4627
       1  4900.5    5055
Encroach Node=4615
       1  4900.5    5055
Encroach Node=4603
       1  4900.5    5055
Encroach Node=4580
       1  4918.6  5095.5
Encroach Node=4548.5
       1  4918.6  5095.5
Encroach Node=4517
       1  4918.6  5095.5
Encroach Node=4414
       1 4929.19  5082.4
Encroach Node=3258
       1 4928.61 5073.99
Encroach Node=3153
       1 4877.76 5126.65
Encroach Node=3122
       1 4877.76 5126.65
Encroach Node=3091
       1 4877.76 5126.65
Encroach Node=2990
       1  4885.7  5115.7
Encroach Node=2732
       13448.3483688.976
Encroach Node=2638.5
       13448.3483688.976
Encroach Node=2545
       13448.3483688.976
Encroach Node=2442
       1 4940.99    5151
Encroach Node=1770
       1 4851.25  5068.7
BEGIN DESCRIPTION:
Post-Project March 2018+ LOMR 08-06-1092P
+ Revised LOMR 15-06-1734P
+ Revised LOMR 17-06-3887P
+ Revised LOMR 18-06-2182P
END DESCRIPTION:
Computation Interval=1HOUR
Output Interval=1HOUR
Run HTab= 0
Run UNet= 0
Run PostProcess= 0
UNET Theta= 1
UNET ZTol= 0.02
UNET ZSATol= 0.1
UNET MxIter= 20
UNET MaxInSteps= 20
UNET DtIC= 0
UNET DtMin= 0
UNET MaxCRTS= 20
UNET WFStab= 2
UNET SFStab= 1
UNET WFX= 1
UNET SFX= 1
UNET Convert EG Bridges=-1
UNET Use Existing IB Tables=-1
Instantaneous Interval=1HOUR
DSS File=dss
Write IC File= 0
IC Time=0
Write Velocity= 0
Write Detailed= 0

--- K142-00-00.p01 (plan) ---

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Plan Title=Effective Multi-profile-2018
Short Identifier=Eff+LOMR MP
Geom File=g01
Flow File=f01
Encroach Param=-1 ,0,0, 0

--- K142-00-00.f02 (steady flow) ---

Flow Title=Floodway
Program Version=4.10
Number of Profiles= 2
Profile Names=1PCT_100yr, 1PCTFloodway_100yrFW
River Rch & RM=K142-00-00,K142-00-00_0018 ,30832
    1530    1530
River Rch & RM=K142-00-00,K142-00-00_0018 ,28776
    1800    1800
River Rch & RM=K142-00-00,K142-00-00_0018 ,26704
    2050    2050
River Rch & RM=K142-00-00,K142-00-00_0018 ,24428
    2250    2250
River Rch & RM=K142-00-00,K142-00-00_0018 ,22833
    2400    2400
River Rch & RM=K142-00-00,K142-00-00_0018 ,20528
    4350    4350
River Rch & RM=K142-00-00,K142-00-00_0018 ,19638
    4460    4460
River Rch & RM=K142-00-00,K142-00-00_0018 ,18737
    4610    4610
River Rch & RM=K142-00-00,K142-00-00_0018 ,17620
    4730    4730
River Rch & RM=K142-00-00,K142-00-00_0018 ,16692
    4840    4840
River Rch & RM=K142-00-00,K142-00-00_0018 ,15926
    5090    5090
River Rch & RM=K142-00-00,K142-00-00_0018 ,14144
    5330    5330
River Rch & RM=K142-00-00,K142-00-00_0018 ,12468
    5530    5530
River Rch & RM=K142-00-00,K142-00-00_0018 ,11266
    5870    5870
River Rch & RM=K142-00-00,K142-00-00_0018 ,9136
    6060    6060
River Rch & RM=K142-00-00,K142-00-00_0018 ,8016
    6200    6200
River Rch & RM=K142-00-00,K142-00-00_0018 ,7229
    6310    6310
River Rch & RM=K142-00-00,K142-00-00_0018 ,6591
    6490    6490
River Rch & RM=K142-00-00,K142-00-00_0018 ,5595
    6700    6700
River Rch & RM=K142-00-00,K142-00-00_0018 ,4517
    6960    6960
River Rch & RM=K142-00-00,K142-00-00_0018 ,3153
    7240    7240
River Rch & RM=K142-00-00,K142-00-00_0018 ,1770
    7613    7613
Boundary for River Rch & Prof#=K142-00-00,K142-00-00_0018 , 1
Up Type= 0
Dn Type= 3
Dn Slope=0.0029
Boundary for River Rch & Prof#=K142-00-00,K142-00-00_0018 , 2
Up Type= 0
Dn Type= 1
Dn Known WS=116.34
DSS Import GetInterval= 0
DSS Import GetPeak= 0
DSS Import FillOption= 0

--- K142-00-00.f01 (steady flow) ---

Flow Title=FEMA Effective June 2007
Version=Version 3.0.1  May 2012
Number of Profiles= 4
Profile Names=10PCT_10yr, 2PCT_50yr, 1PCT_100yr, 0.2PCT_500yr
River Rch & RM=K142-00-00,K142-00-00_0018 ,30832
     790    1300    1530    2190
River Rch & RM=K142-00-00,K142-00-00_0018 ,28776
     930    1600    1800    2600
River Rch & RM=K142-00-00,K142-00-00_0018 ,26704
    1080    1770    2050    2980
River Rch & RM=K142-00-00,K142-00-00_0018 ,24428
    1210    1900    2250    3280
River Rch & RM=K142-00-00,K142-00-00_0018 ,22833
    1300    2000    2400    3500
River Rch & RM=K142-00-00,K142-00-00_0018 ,20528
    2320    3660    4350    6390
River Rch & RM=K142-00-00,K142-00-00_0018 ,19638
    2370    3760    4460    6550
River Rch & RM=K142-00-00,K142-00-00_0018 ,18737
    2440    3880    4610    6750
River Rch & RM=K142-00-00,K142-00-00_0018 ,17620
    2510    3980    4730    6930
River Rch & RM=K142-00-00,K142-00-00_0018 ,16692
    2560    4070    4840    7080
River Rch & RM=K142-00-00,K142-00-00_0018 ,15926
    2680    4280    5090    7430
River Rch & RM=K142-00-00,K142-00-00_0018 ,14144
    2800    4490    5330    7780
River Rch & RM=K142-00-00,K142-00-00_0018 ,12468
    2900    4650    5530    8050
River Rch & RM=K142-00-00,K142-00-00_0018 ,11266
    3070    4930    5870    8540
River Rch & RM=K142-00-00,K142-00-00_0018 ,9136
    3160    5090    6060    8810
River Rch & RM=K142-00-00,K142-00-00_0018 ,8016
    3230    5210    6200    9000
River Rch & RM=K142-00-00,K142-00-00_0018 ,7229
    3280    5300    6310    9160
River Rch & RM=K142-00-00,K142-00-00_0018 ,6591
    3370    5450    6490    9410
River Rch & RM=K142-00-00,K142-00-00_0018 ,5595
    3470    5620    6700    9700
River Rch & RM=K142-00-00,K142-00-00_0018 ,4517
    3600    5850    6960   10080
River Rch & RM=K142-00-00,K142-00-00_0018 ,3153
    3730    6070    7240   10460
River Rch & RM=K142-00-00,K142-00-00_0018 ,1770
    3916    6386    7613   10986
Boundary for River Rch & Prof#=K142-00-00,K142-00-00_0018 , 1
Up Type= 0
Dn Type= 3
Dn Slope=.0029
Boundary for River Rch & Prof#=K142-00-00,K142-00-00_0018 , 2
Up Type= 0
Dn Type= 3
Dn Slope=.0029
Boundary for River Rch & Prof#=K142-00-00,K142-00-00_0018 , 3
Up Type= 0
Dn Type= 3
Dn Slope=.0029
Boundary for River Rch & Prof#=K142-00-00,K142-00-00_0018 , 4
Up Type= 0
Dn Type= 3
Dn Slope=.0029
DSS Import GetInterval= 0
DSS Import GetPeak= 0
DSS Import FillOption= 0

--- K142-00-00.g01 (geometry) ---

Geom Title=K142-00-00 Effective 2018
Program Version=5.03

River Reach=K142-00-00      ,K142-00-00_0018
Reach XY= 30
      3027479.25     13936136.39      3027939.75       13936130.
      3030198.25       13934322.      3030916.86     13934200.49
       3031447.3     13933781.56      3033368.31     13933719.06
       3033966.4     13933403.09      3034695.57      13933324.1
      3035964.67     13932527.22      3036412.58     13932502.05
      3037206.44     13930847.89      3037269.98     13929731.74
      3037626.25       13928400.      3038347.41     13927538.92
      3039298.09     13927178.12      3040326.82     13927086.18
      3041842.37     13926676.14        3043609.       13925778.
      3044075.64      13924531.2      3044076.81     13924072.03
      3044391.86      13923803.1      3045303.41     13923457.85
      3046361.56     13923489.44        3047335.       13922957.
      3048070.73     13923071.11      3048376.65     13922895.15
      3048756.74     13922122.22      3049633.38     13921962.05
      3049899.87     13922357.01      3050250.72      13921982.6

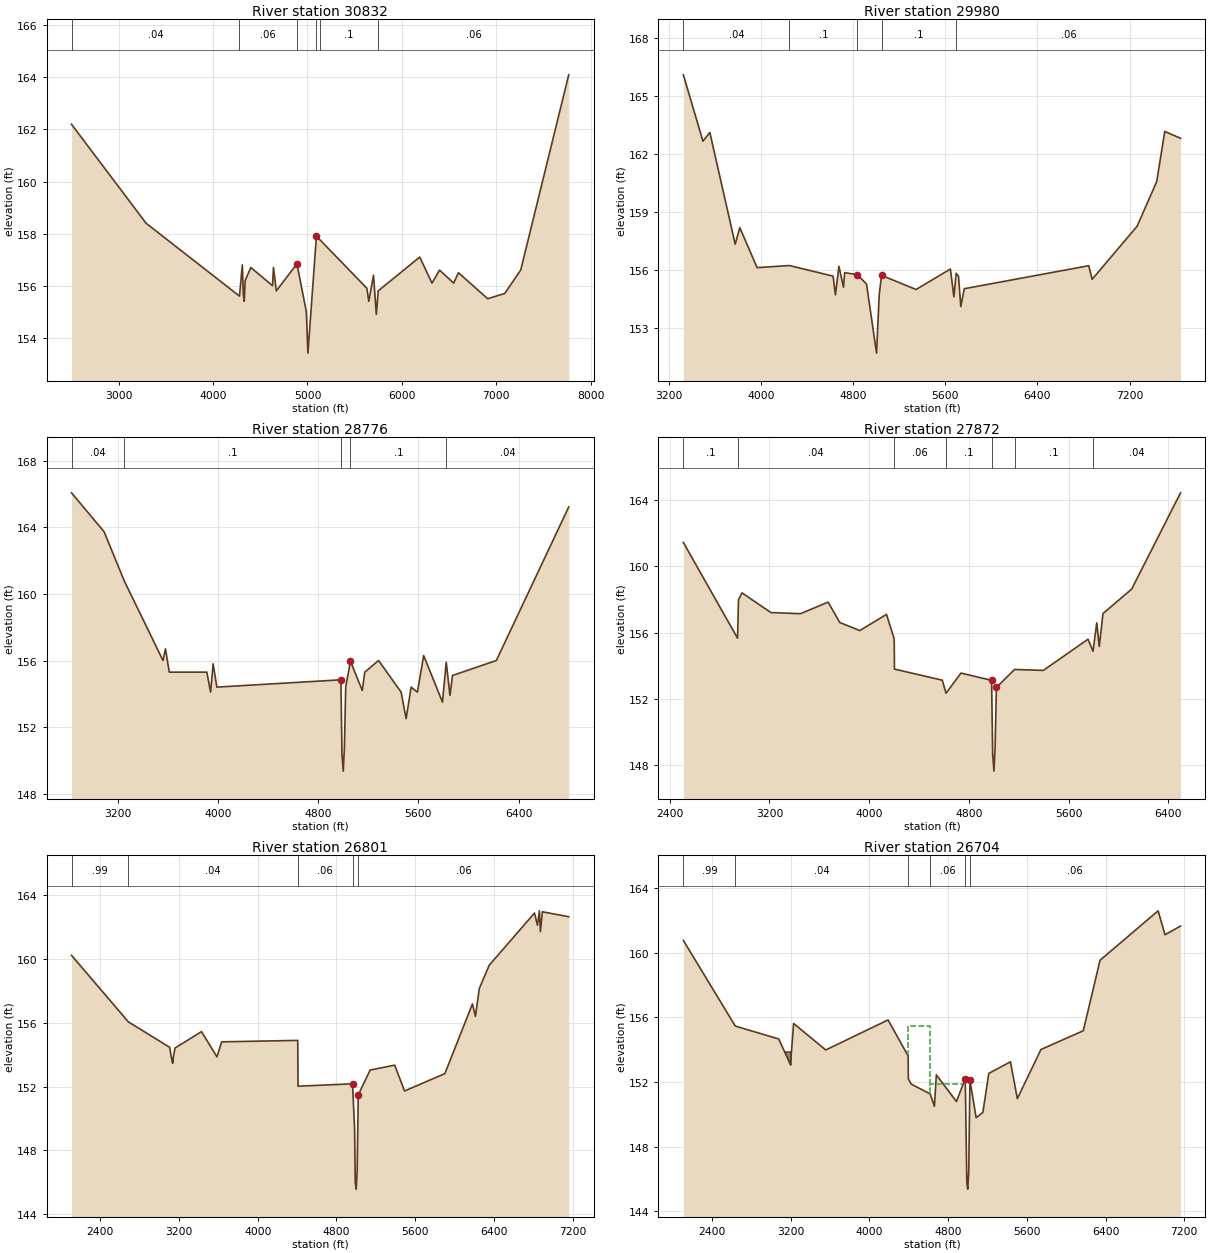
Type RM Length L Ch R = 1 ,30832   ,907.2,852,604.2
BEGIN DESCRIPTION:
Cross Section K142-00-00-X13
END DESCRIPTION:
XS GIS Cut Line= 2
       3027738.8       13938627.      3027341.68     13933373.42
#Sta/Elev= 30
  2499.9   162.2  3289.9   158.4  4279.9   155.6  4309.9   156.8  4319.9   155.7
  4329.9   155.4  4339.9   156.2  4399.9   156.7  4629.9     156  4639.9   156.7
  4669.9   155.8  4888.6  156.84  4988.2     155  5004.9  153.41    5095   157.9
  5135.7  157.75  5629.9   155.9  5649.9   155.4  5699.9   156.4  5729.9   154.9
  5749.9   155.8  6189.9   157.1  6319.9   156.1  6399.9   156.6  6549.9   156.1
  6599.9   156.5  6909.9   155.5  7089.9   155.7  7259.9   156.6  7768.8   164.1
#Mann= 6 ,-1 , 0
  2499.9     .04       0  4279.9     .06       0  4888.6    .055       0
    5095     .06       0  5135.7      .1       0  5749.9     .06       0
Bank Sta=4888.6,5095
XS Rating Curve= 0 ,0
Exp/Cntr=0.3,0.1

Type RM Length L Ch R = 1 ,29980   ,1101,1204,1209.3
BEGIN DESCRIPTION:
interpolated XS
END DESCRIPTION:
XS GIS Cut Line= 4
      3028956.69     13937367.63      3028493.67     13936304.35
      3027981.67     13935299.41      3027619.73     13933305.06
#Sta/Elev= 30
  3328.4  166.11  3498.4  162.68  3558.4  163.13  3778.4  157.35  3818.4  158.21
  3968.4  156.14  4248.4  156.25  4628.1   155.7  4648.1  154.73  4678.1  156.21
  4718.1  155.13  4728.1  155.88  4838.1  155.78  4918.1  155.29  5004.9  151.72
  5028.1  154.74  5048.1  155.74  5348.1  155.01    5646  156.07    5676  154.63
    5696  155.85    5716   155.7    5736  154.13    5766  155.05    6846  156.24
    6876  155.54    7266  158.28    7436  160.59    7506  163.18  7642.9  162.83
#Mann= 5 ,-1 , 0
  3328.4     .04       0  4248.4      .1       0  4838.1    .055       0
  5048.1      .1       0    5696     .06       0
Bank Sta=4838.1,5048.1
XS Rating Curve= 0 ,0
Exp/Cntr=0.3,0.1

Type RM Length L Ch R = 1 ,28776   ,950.1,904,795.8
BEGIN DESCRIPTION:
Cross Section K142-00-00-X12
END DESCRIPTION:
XS GIS Cut Line= 4
        3029362.       13937300.      3029197.83     13935186.51
      3029191.66     13935106.38      3028613.38     13933435.96
#Sta/Elev= 30
    2832  166.08    3092  163.74    3252   160.8    3562     156    3582   156.7
    3612   155.3    3912   155.3    3942   154.1    3962   155.8    3992   154.4
  4981.7  154.84  4990.4  150.37  5000.6  149.35  5009.6   150.7  5020.3  154.41
  5057.9  155.96  5152.4   154.2  5172.4   155.3  5282.4     156  5462.4   154.1
  5502.4   152.5  5542.4   154.4  5592.4   154.1  5642.4   156.3  5792.4   153.5
  5822.4   155.9  5852.4   153.9  5872.4   155.1  6222.4     156  6800.1  165.23
#Mann= 5 ,-1 , 0
    2832     .04       0    3252      .1       0  4981.7    .055       0
  5057.9      .1       0  5822.4     .04       0
Bank Sta=4981.7,5057.9
XS Rating Curve= 0 ,0
Exp/Cntr=0.3,0.1

Type RM Length L Ch R = 1 ,27872   ,789.4,1071,1185.9
BEGIN DESCRIPTION:
interpolated XS
END DESCRIPTION:
XS GIS Cut Line= 4
       3030086.8      13936990.9      3030182.84     13935107.36
      3029651.02     13934250.53      3029217.55     13933248.46
#Sta/Elev= 30
  2510.4  161.45    2945  155.66 2952.52  157.98 2980.49   158.4 3212.24  157.21
 3449.02  157.14  3671.2  157.84 3764.17  156.61 3925.12  156.12 4139.06   157.1
 4200.04  155.64 4201.04   155.5 4203.04  153.79  4586.4  153.12  4616.4  152.33
  4736.4  153.55  4981.7  153.11  4990.4  148.64  5000.6  147.62  5009.6  148.97
  5020.3  152.68  5166.4  153.77  5396.4  153.71  5754.9   155.6  5794.9  154.87
  5824.9  156.59  5844.9  155.16  5874.9  157.15  6104.9  158.63  6496.7  164.45
#Mann= 7 ,-1 , 0
  2510.4      .1       0 2952.52     .04       0 4200.04     .06       0
  4616.4      .1       0  4981.7    .055       0  5166.4      .1       0
  5794.9     .04       0
Bank Sta=4981.7,5020.3
XS Rating Curve= 0 ,0
Exp/Cntr=0.3,0.1

Type RM Length L Ch R = 1 ,26801   ,93.7,97,98.3
BEGIN DESCRIPTION:
K142-00-00-S8_SHAW RD - US - XS4
Added Ineffective Flow per CI DIA March 2013
END DESCRIPTION:
XS GIS Cut Line= 4
      3030792.94      13937127.7      3030812.81     13934403.45
      3030821.23     13934095.18      3030022.11     13932242.29
#Sta/Elev= 30
  2108.9  160.22 2686.61  156.05 3105.41  154.46  3133.4  153.48 3159.39  154.41
 3429.26  155.44 3586.19  153.86 3634.03   154.8 4407.01  154.89 4410.01  152.02
  4963.2  152.17 4984.09  149.42 4991.04  146.01 5000.05  145.57 5010.25  146.68
 5021.43  151.47  5141.6  153.03  5391.6  153.34  5491.6  151.72  5901.6  152.81
  6181.6  157.18  6211.6   156.4  6251.6  158.15  6351.6   159.6  6811.6  162.87
  6841.6  162.11  6861.6  163.01  6871.6  161.71  6891.6  162.95  7159.5  162.64
#Mann= 5 ,-1 , 0
  2108.9     .99       0 2686.61     .04       0 4407.01     .06       0
  4963.2    .055       0 5021.43     .06       0
#XS Ineff= 2 , 0
       0    4865  151.91  5132.4       0   151.5
Permanent Ineff=
       F       F
#Block Obstruct= 1 ,-1
    3130    3150  153.72
Bank Sta=4963.2,5021.43
XS Rating Curve= 0 ,0
Exp/Cntr=0.5,0.3

Type RM Length L Ch R = 1 ,26704   ,50.4,55,58.9
BEGIN DESCRIPTION:
K142-00-00-S8_SHAW RD - US - XS3
Added Ineffective Flow per CI DIA March 2013
END DESCRIPTION:
XS GIS Cut Line= 4
       3030884.2       13937092.      3030904.08     13934367.95
      3030912.51     13934059.68      3030113.38     13932206.79
#Sta/Elev= 30
  2111.3  160.77 2638.87  155.47  3080.5  154.67 3199.41  153.08 3231.38  155.63
 3557.69  153.99 4191.03  155.85 4394.85  153.62 4396.84  152.21 4425.82  151.88
 4618.65  151.27  4661.3  150.51  4681.3  152.45  4885.6   150.8    4975  152.22
  4990.8   145.8    5000  145.38  5010.3  146.46  5022.4  152.12  5085.6   149.8
    5154  150.13    5214  152.54    5434  153.26    5504  150.98    5744  154.02
    6174  155.18    6344  159.54    6934   162.6    7004  161.12  7161.9  161.66
#Mann= 6 ,-1 , 0
  2111.3     .99       0 2638.87     .04       0 4394.85     .04       0
 4618.65     .06       0    4975    .055       0  5022.4     .06       0
#XS Ineff= 3 ,-1
  4394.8    4619  155.48    4619    4965  151.91  5032.4    7500   151.5
Permanent Ineff=
       T       F       F
#Block Obstruct= 1 ,-1
    2950    3200   153.9
Bank Sta=4975,5022.4
XS Rating Curve= 0 ,0
Exp/Cntr=0.5,0.3

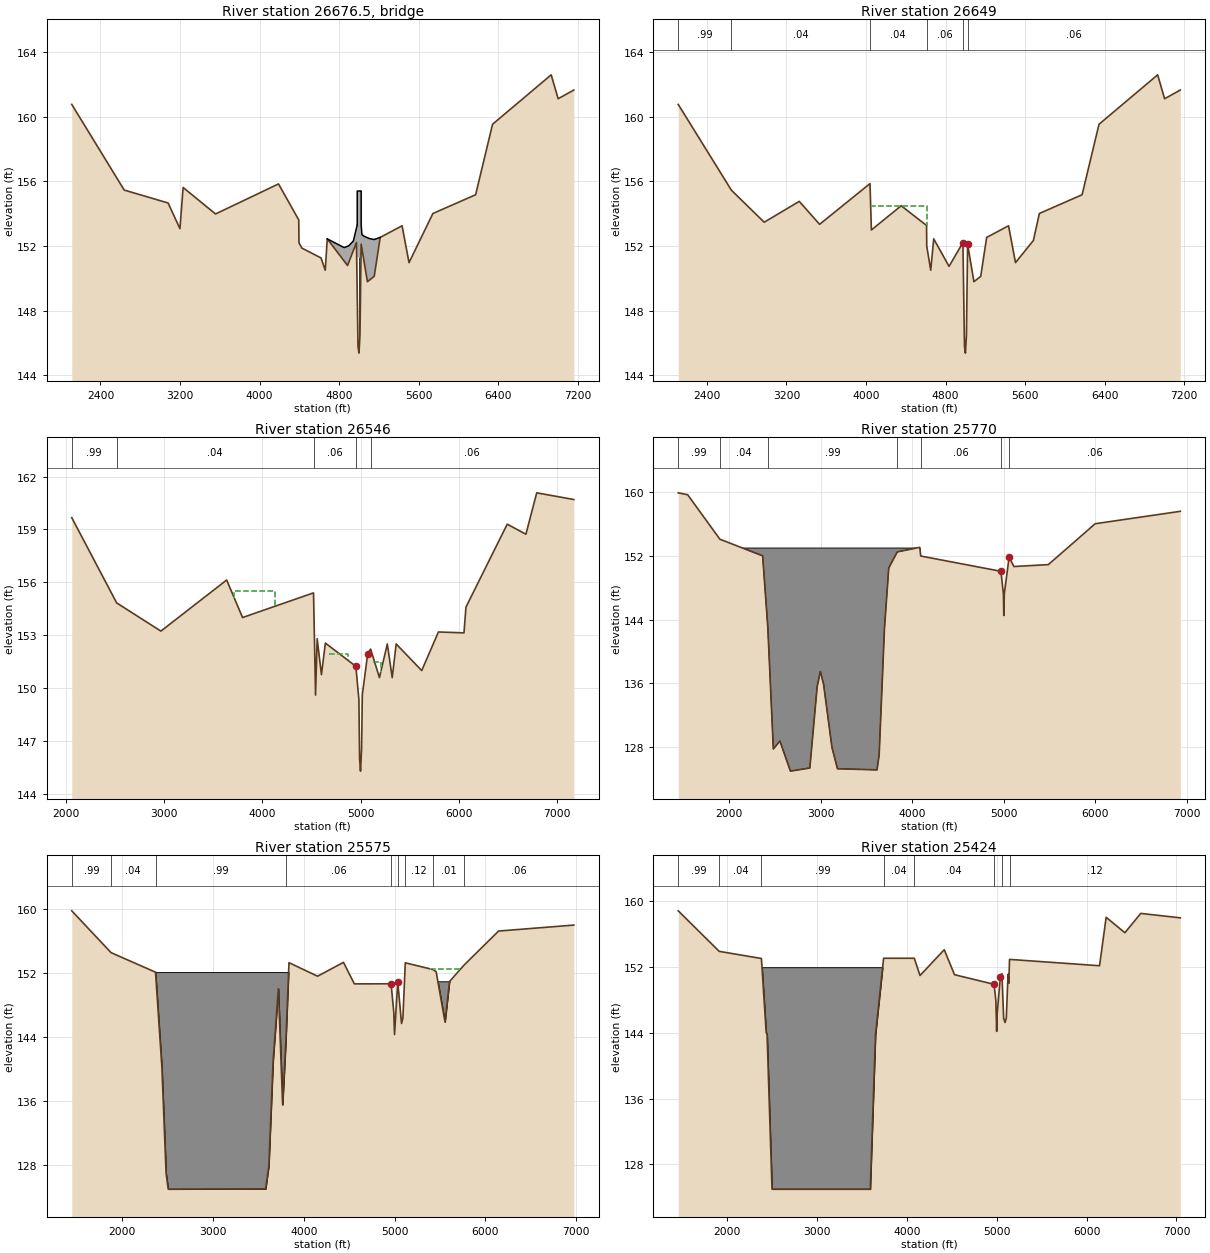
Type RM Length L Ch R = 3 ,26676.5 ,,,
BEGIN DESCRIPTION:
SHAW ROAD
Structure ID: K142-00-00-S8
END DESCRIPTION:
Bridge Culvert--1,0,-1,-1, 0
Deck Dist Width WeirC Skew NumUp NumDn MinLoCord MaxHiCord MaxSubmerge Is_Ogee
10,31,2.6,0, 39, 39, , , 0.95, 0, ,,,
  4681.3  4851.2  4896.9  4898.2  4943.4  4943.6    4975  4982.5 4982.61  4982.7
 4982.79  4982.9 4983.01  4983.7  4985.1  4987.1  4988.6  4990.8    5000  5002.7
  5010.3  5011.4  5014.8 5017.09  5017.2  5017.3  5021.6  5022.4 5022.49  5022.6
 5022.71  5030.4    5058  5059.1  5105.3  5105.6  5152.5  5152.7    5214
  152.45  151.91  152.02  152.03  152.31  152.31  153.12  153.31  153.31  153.31
  153.31  155.41  155.41  155.41  155.41  155.41  155.41  155.41  155.41  155.41
  155.41  155.41  155.41  155.41  155.41  155.41  155.41  155.41  155.41  155.41
  153.31  152.71  152.59  152.59  152.47  152.47  152.41  152.41  152.54
     150     150     150     150  151.65  151.65   152.2  149.76  149.72  151.31
  151.31  151.31  151.31  151.31  151.31  151.31  151.31  151.31  151.31  151.31
  151.31  151.31  151.31  151.31   149.6  149.64  151.36   152.1   152.1   152.1
   152.1     149     149     149     149     149     149     149  152.54
  4681.3  4851.2  4896.9  4898.2  4943.4  4943.6    4975  4982.5 4982.61  4982.7
 4982.79  4982.9 4983.01  4983.7  4985.1  4987.1  4988.6  4990.8    5000  5002.7
  5010.3  5011.4  5014.8 5017.09  5017.2  5017.3  5021.6  5022.4 5022.49  5022.6
 5022.71  5030.4    5058  5059.1  5105.3  5105.6  5152.5  5152.7    5214
  152.45  151.91  152.02  152.03  152.31  152.31  153.12  153.31  153.31  153.31
  153.31  155.41  155.41  155.41  155.41  155.41  155.41  155.41  155.41  155.41
  155.41  155.41  155.41  155.41  155.41  155.41  155.41  155.41  155.41  155.41
  153.31  152.71  152.59  152.59  152.47  152.47  152.41  152.41  152.54
     150     150     150     150  151.65  151.65   152.2  149.76  149.72  151.31
  151.31  151.31  151.31  151.31  151.31  151.31  151.31  151.31  151.31  151.31
  151.31  151.31  151.31  151.31   149.6  149.64  151.36   152.1   152.1   152.1
   152.1     149     149     149     149     149     149     149  152.54
Pier Skew, UpSta & Num, DnSta & Num=  ,5002.7, 2 ,5002.7, 2 , 0 , 0 , 0 ,,
       1       1
  144.64  152.31
       1       1
  145.06  152.73
BR Coef= 1 , 1 , 1 ,1.25, 0 ,,,0.8,0,2,0,
WSPro=,,,, 1 ,,,, 0 ,,,, 0 ,,,,-1 ,-1 ,-1 , 0 , 0 , 0 , 0 , 0
BC Design=,, 0 ,, 0 ,,,,,,
BC HTab HWMax=162.6
BC Use User HTab Curves=0
BC User HTab FreeFlow(D)= 0

Type RM Length L Ch R = 1 ,26649   ,101.9,103,53.1
BEGIN DESCRIPTION:
K142-00-00-S8_SHAW RD - DS - XS2
Added Ineffective Flow per CI DIA March 2013
END DESCRIPTION:
XS GIS Cut Line= 4
        3030936.       13937113.      3030951.93     13934351.76
       3030960.6     13934034.41      3030175.88     13932154.71
#Sta/Elev= 30
  2111.3  160.77 2646.18  155.46  2976.1  153.48 3328.78  154.77 3533.36  153.35
 4040.33  155.87 4054.32     153  4354.1   154.5 4609.29  153.28 4611.29     152
  4651.3  150.51  4681.3  152.45  4835.6  150.75    4975  152.22  4990.8   145.8
    5000  145.38  5010.3  146.46  5022.4  152.12  5085.6   149.8    5154  150.13
    5214  152.54    5434  153.26    5504  150.98    5684  152.35    5744  154.02
    6174  155.18    6344  159.54    6934   162.6    7004  161.12  7161.9  161.66
#Mann= 6 ,-1 , 0
  2111.3     .99       0 2646.18     .04       0 4040.33     .04       0
 4609.29     .06       0    4975    .055       0  5022.4     .06       0
#XS Ineff= 3 ,-1
    4040  4609.3   154.5  4609.3  4968.3   151.5    5029    7500   151.5
Permanent Ineff=
       T       F       F
Bank Sta=4975,5022.4
XS Rating Curve= 0 ,0
Exp/Cntr=0.5,0.3

Type RM Length L Ch R = 1 ,26546   ,720.5,776,811.1
BEGIN DESCRIPTION:
K142-00-00-S8_SHAW RD - DS - XS1
Added Ineffective Flow per CI DIA March 2013
END DESCRIPTION:
XS GIS Cut Line= 4
      3031019.96      13937049.6      3031054.83     13934143.93
      3031025.73     13934086.89      3030259.54     13932091.33
#Sta/Elev= 30
  2062.6  159.67 2519.48  154.83 2969.37  153.23 3638.32  156.13    3800     154
    4522   155.4  4542.6   149.6    4559   152.8  4602.6  150.76  4642.6  152.55
  4952.6  151.23  4983.5  149.35 4990.69  145.99 5000.02  145.28 5011.02  146.57
 5018.38  149.61  5072.6  151.93  5102.6  152.21  5192.6  150.59  5272.6   152.5
  5322.6  150.59  5362.6   152.5  5622.6  150.99  5792.6  153.18  6052.6  153.13
  6072.6  154.59  6492.6   159.3  6682.6  158.73  6792.6  161.08  7170.2   160.7
#Mann= 5 ,-1 , 0
  2062.6     .99       0 2519.48     .04       0    4522     .06       0
  4952.6     .05       0  5102.6     .06       0
#XS Ineff= 3 ,-1
    4684 4868.33  151.91 5129.07    5206   151.5 3716.27    4127  155.48
Permanent Ineff=
       F       F       T
Bank Sta=4952.6,5072.6
XS Rating Curve= 0 ,0
Exp/Cntr=0.3,0.1

Type RM Length L Ch R = 1 ,25770   ,130,195,247
BEGIN DESCRIPTION:
New C/S
END DESCRIPTION:
XS GIS Cut Line= 4
 3031742.930353413937251.7429719 3031742.930353413933931.7151631
 3031632.912200713933509.6677788 3031513.240524113931784.5905204
#Sta/Elev= 30
  1443.1  159.93 1546.14  159.69 1898.27 154.108 2365.34 152.022 2421.91 143.025
 2482.11 127.781    2554 128.773 2668.94     125 2880.95 125.392 2960.87 135.597
  2995.9   137.5 3030.93 135.916 3122.53  127.98 3182.73   125.3 3614.78 125.156
 3638.13 127.024 3696.52 142.936 3743.23 150.501 3836.64 152.517 4081.86 153.089
 4092.34     152    4969  150.08 4996.46  147.15    5000  144.53 5006.04  147.28
 5057.94  151.84 5110.88  150.68 5486.61  150.92 5998.36  156.05  6928.5  157.61
#Mann= 7 ,-1 , 0
  1443.1     .99       0 1898.27     .04       0 2421.91     .99       0
 3836.64     .04       0 4092.34     .06       0    4969     .05       0
 5057.94     .06       0
#Block Obstruct= 2 ,-1
    2092    4085     153    4980    5020     130
Bank Sta=4969,5057.94
XS Rating Curve= 0 ,0
Exp/Cntr=0.3,0.1

Type RM Length L Ch R = 1 ,25575   ,149,151,155
XS GIS Cut Line= 5
 3031829.935852513937252.9006576 3031874.746692813933940.4750543
 3031878.3254946 13933557.543258  3031871.16789113933077.9838121
 3031838.958674513931718.0391149
#Sta/Elev= 30
 1441.54 159.813 1874.55 154.584 2365.03 152.136 2435.09 140.281 2481.81 126.951
 2505.16     125 3579.54 125.037 3614.58 127.937 3661.29 140.994 3719.68 150.069
 3766.39  135.55 3801.43 143.343 3836.46 153.329 4151.77 151.633 4437.21 153.369
 4557.23 150.675 4962.25 150.685 4992.25 147.087    5000  144.34 5035.85150.9209
 5077.25  145.72 5092.25  146.37 5118.77153.3106 5423.88 152.468 5458.92 152.204
 5556.91 145.909  5605.9 150.957 5765.17  153.01 6147.46 157.283 6977.16 158.031
#Mann= 9 ,-1 , 0
 1441.54     .99       0 1874.55     .04       0 2365.03     .99       0
 3801.43     .06       0 4962.25    .055       0 5035.85    .035       0
 5118.77     .12       0 5423.88     .01       0 5765.17     .06       0
#XS Ineff= 1 ,-1
 5396.54 5720.64  152.58
Permanent Ineff=
       F
#Block Obstruct= 2 ,-1
 2360.19    3840  152.15 5396.54 5720.64     151
Bank Sta=4962.25,5035.85
XS Rating Curve= 0 ,0
Exp/Cntr=0.3,0.1

Type RM Length L Ch R = 1 ,25424   ,399,352,362
BEGIN DESCRIPTION:
interpolated XS
Prop FP fill to 152 (CI)
Pond C 100 year- 149.63' (CI- DIA)
END DESCRIPTION:
XS GIS Cut Line= 3
       3031967.5       13937258.      3032036.85     13933016.98
      3032009.21     13931675.54
#Sta/Elev= 30
  1458.4  158.86 1914.03  153.93 2383.64  153.06  2436.6  144.08 2446.59  143.81
 2501.55     125 3594.53     125 3652.51   143.8 3742.48  153.09 4083.87  153.09
 4147.45  150.99 4417.13  154.13  4531.1  151.09  4971.1  149.92  4991.1  147.95
  5000.2  144.19  5005.4   146.3  5041.1  150.81  5058.4  151.22    5078  145.78
    5093  145.27    5107145.7799 5126.57  151.145135.511  150.045142.964 152.952
  6144.3 152.179  6217.8 158.075 6426.06 156.193 6602.61 158.547  7042.6 158.007
#Mann= 8 ,-1 , 0
  1458.4     .99       0 1914.03     .04       0 2383.64     .99       0
 3742.48     .04       0 4083.87     .04       0  4971.1    .055       0
  5058.4    .035       05142.964     .12       0
#Block Obstruct= 2 , 0
       0    3746     152               0
Bank Sta=4971.1,5041.1
XS Rating Curve= 0 ,0
Exp/Cntr=0.3,0.1

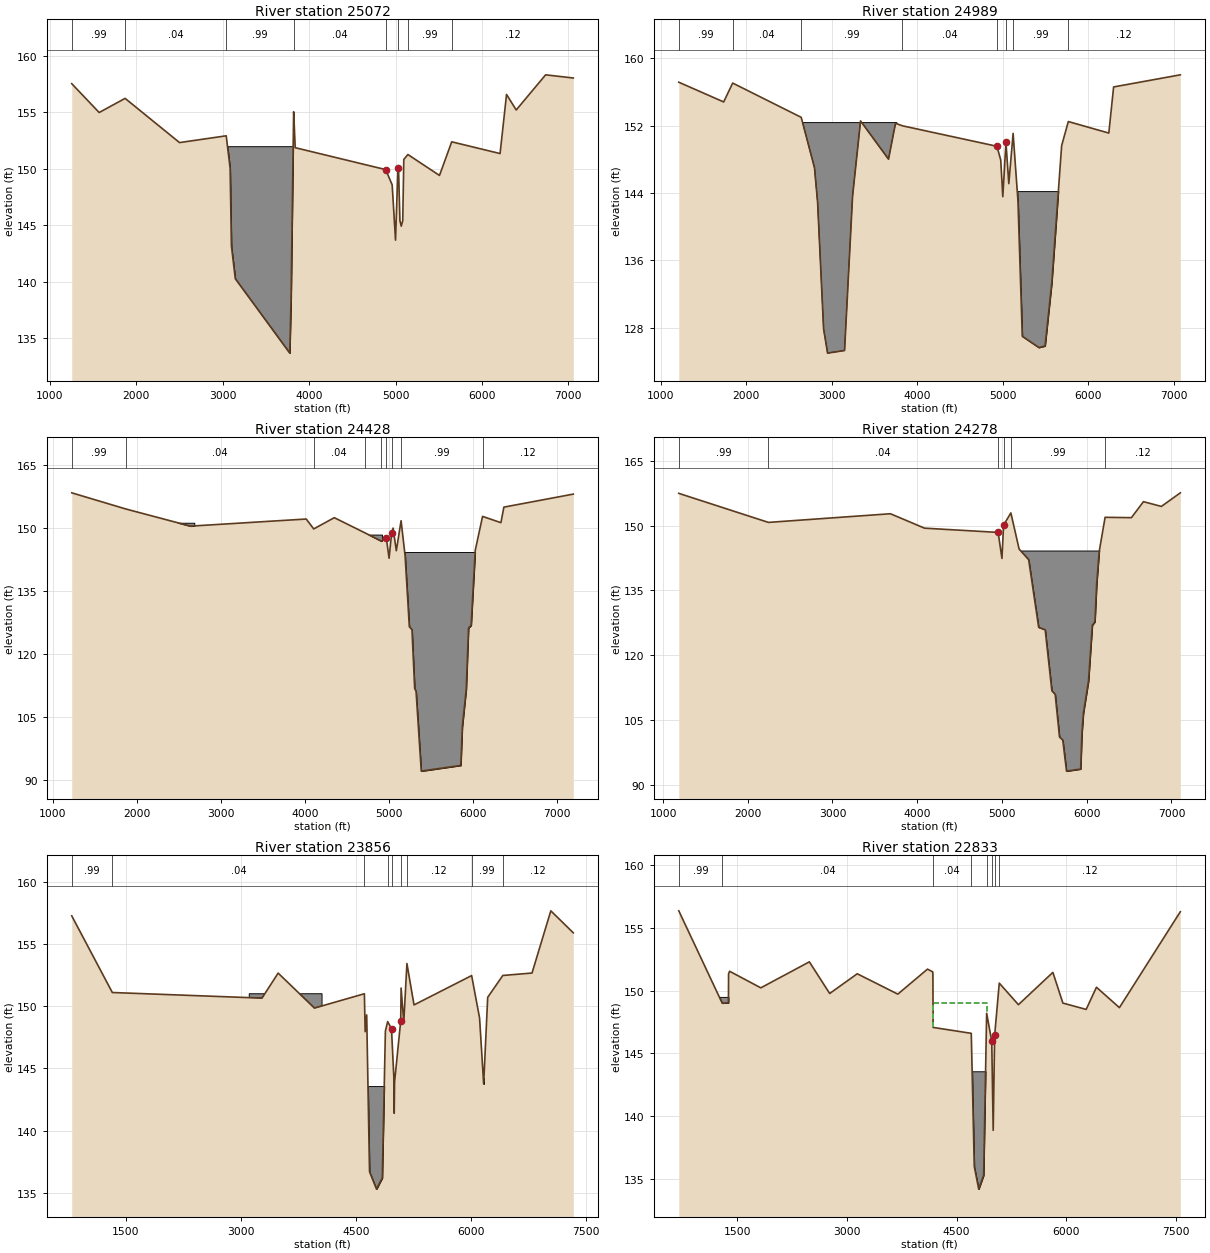
Type RM Length L Ch R = 1 ,25072   ,90,83,80
XS GIS Cut Line= 6
 3032475.802017213937469.8711288 3032377.434134413933898.1341503
 3032378.809951513933718.6300006 3032391.465545113933232.1755778
 3032363.181179613933059.5658386 3032105.982715913931692.7227894
#Sta/Elev= 30
 1252.59  157.53 1570.08  154.98 1870.19  156.23 2500.43  152.32 3040.64  152.92
 3085.66  150.06 3100.66  143.18 3145.68  140.28 3775.92   133.7 3790.92  138.34
 3820.93  155.05 3823.41   154.7 3838.84  151.87 4886.32  149.93 4961.32  148.58
    5000  143.69 5027.89150.0358 5033.93150.2889    5051  145.41  5066.5  144.93
  5083.5  145.41 5095.77150.8322 5143.41151.2635 5508.91149.4153 5650.47152.3887
 6210.14  151.35 6284.92 156.577 6397.08 155.204 6737.25 158.313 7057.55 158.031
#Mann= 8 ,-1 , 0
 1252.59     .99       0 1870.19     .04       0 3040.64     .99       0
 3823.41     .04       0 4886.32    .055       0 5027.89    .035       0
 5143.41     .99       0 5650.47     .12       0
#Block Obstruct= 2 ,-1
 3029.73 3816.81     152  5167.7 5577.72  144.23
Bank Sta=4886.32,5027.89
XS Rating Curve= 0 ,0
Exp/Cntr=0.3,0.1

Type RM Length L Ch R = 1 ,24989   ,591,561,399.8
BEGIN DESCRIPTION:
New C/S
END DESCRIPTION:
XS GIS Cut Line= 6
 3032595.657322413937519.8293779 3032473.812093713934261.6465899
 3032460.859363613933915.2873744 3032461.894794713933734.1118838
 3032475.732365413933243.1624063 3032156.831756413931688.6418934
#Sta/Elev= 30
 1210.15 157.154 1735.26 154.813 1840.43 157.053 2642.02 152.987 2797.41 146.996
 2833.66 142.917 2903.77 127.888 2950.51     125 3149.16 125.309 3242.64 143.597
 3336.12  152.56 3663.31 148.017  3745.1 152.283 3824.73 151.983 4930.99  149.55
 4975.74  147.93    5000  143.575036.883150.00625070.147  145.125120.634151.0779
5177.492143.0001  5227.8     1275421.287125.66685494.454125.84625573.252133.3701
5688.162 149.6325766.273152.48416239.851151.11916296.117156.5922 7076.43 158.031
#Mann= 8 ,-1 , 0
 1210.15     .99       0 1840.43     .04       0 2642.02     .99       0
 3824.73     .04       0 4930.99    .055       05036.883    .035       0
5120.634     .99       05766.273     .12       0
#Block Obstruct= 2 ,-1
    2642    3761  152.36    5117 5737.53  144.23
Bank Sta=4930.99,5036.883
XS Rating Curve= 0 ,0
Exp/Cntr=0.3,0.1

Type RM Length L Ch R = 1 ,24428   ,213.7,150,156
BEGIN DESCRIPTION:
Cross Section K142-00-00-X11
Prop FP fill to 151 (CI)
END DESCRIPTION:
XS GIS Cut Line= 4
       3033248.8       13937508.      3033026.14     13933786.19
      3033013.55     13933655.49      3032363.88     13931649.12
#Sta/Elev= 30
  1223.3  158.31 1870.09  154.45  2636.7  150.39 4014.45  152.08  4103.3  149.73
  4348.3   152.4  4709.1  148.83  4909.6  146.81  4967.4   147.6  5000.2  142.76
  5030.9  148.725047.993149.91615086.483  144.545143.078151.68085191.036143.3833
 5241.19126.49795272.959125.75245304.976111.80225321.631111.0728 5383.36 92.1355
5854.383 93.49015872.073 102.6215918.641111.54295946.199126.18865977.188126.8008
6026.047144.63476113.019152.70656331.527151.2138 6366.78154.9099  7192.9 158.004
#Mann= 9 ,-1 , 0
  1223.3     .99       0 1870.09     .04       0  4103.3     .04       0
  4709.1     .01       0  4909.6     .04       0  4967.4    .055       0
  5030.9    .035       05143.078     .99       06113.019     .12       0
#Block Obstruct= 3 ,-1
 4709.09 4915.15  148.38    2420    2682   151.2    5125 6104.79  144.23
Bank Sta=4967.4,5030.9
XS Rating Curve= 0 ,0
Exp/Cntr=0.3,0.1

Type RM Length L Ch R = 1 ,24278   ,554,422,457.8
XS GIS Cut Line= 6
 3033588.446329513937496.3341641 3033294.941391813934742.3678065
 3033177.848382513933775.8488259 3033143.340890513933569.3408582
 3033149.251985213933455.0596939 3032518.366713813931719.6218774
#Sta/Elev= 30
 1186.12 157.474 2243.76 150.742 3683.61 152.749 4086.27 149.406 4954.83 148.423
    5000   142.4 5019.04 150.102  5105.1 152.943 5202.35 144.574 5315.11 142.105
 5433.21 126.428    5510125.85725588.844111.71765627.815110.91285679.035101.0151
5717.698100.28325761.775 93.09985928.823 93.57795943.295101.71485961.323106.5413
6021.436113.94046066.281126.91616097.037 127.7116117.437136.33746147.665     144
  6217.1 151.921 6527.72 151.841 6669.77 155.546  6881.2 154.445 7105.03 157.596
#Mann= 6 ,-1 , 0
 1186.12     .99       0 2243.76     .04       0 4954.83    .055       0
 5019.04    .035       0  5105.1     .99       0  6217.1     .12       0
#Block Obstruct= 1 ,-1
 5114.47 6164.68  144.23
Bank Sta=4954.83,5019.04
XS Rating Curve= 0 ,0
Exp/Cntr=0.3,0.1

Type RM Length L Ch R = 1 ,23856   ,1102.1,1023,994.7
BEGIN DESCRIPTION:
interpolated XS
Prop Wildwood FP fill to 151 & pond B blocked at 143.3 (CI)
END DESCRIPTION:
XS GIS Cut Line= 4
        3034571.       13937717.      3033890.86     13934752.81
      3033403.35     13933039.14      3032780.05     13931435.96
#Sta/Elev= 30
   794.3  157.26 1323.99   151.1 3276.21  150.65 3487.13  152.66 3960.86  149.85
  4612.2     151  4622.2  147.95  4642.2   149.3  4679.2   136.7  4770.2   135.3
    4846   136.2  4886.2     148  4915.9  148.76  4965.9  148.19  4995.9  144.34
  5001.2   141.4  5005.9  143.92  5085.9  148.79  5091.2  151.46    5126   148.7
    5167  153.43 5259.83 150.103 6011.39 152.461 6114.88 149.053 6168.26  143.75
 6220.82 150.712 6418.25 152.469 6799.02 152.665 7044.48 157.664  7337.6 155.896
#Mann= 9 ,-1 , 0
   794.3     .99       0 1323.99     .04       0  4612.2     .01       0
  4915.9     .12       0  4965.9    .055       0  5091.2    .035       0
    5167     .12       0 6011.39     .99       0 6418.25     .12       0
#XS Ineff= 1 ,-1
  4612.2  4915.9     147
Permanent Ineff=
       T
#Block Obstruct= 3 ,-1
    4640    4911  143.58    3110    4060     151 6108.38 6300.88  144.23
Bank Sta=4965.9,5085.9
XS Rating Curve= 0 ,0
Exp/Cntr=0.3,0.1

Type RM Length L Ch R = 1 ,22833   ,481.26,411,397.9
BEGIN DESCRIPTION:
Cross Section K142-00-00-X10
Prop Wildwood FP fill to 151 & pond B blocked at 143.31 (CI)
END DESCRIPTION:
XS GIS Cut Line= 4
       3035446.7       13937592.      3034519.31     13933438.58
      3034497.11     13933332.23      3033259.21     13931165.12
#Sta/Elev= 30
   700.5  156.35 1294.57     149 1379.57  149.03 1381.57  151.33 1395.57  151.54
 1822.55  150.22 2486.54  152.29 2764.53  149.77  3141.5  151.34 3696.47  149.72
 4102.45  151.71 4174.44  151.49 4176.44  151.25 4179.44  147.07  4701.2   146.6
  4742.2     136  4803.2   134.2  4870.7   135.3  4911.5   148.2  4981.1  145.98
  5001.2  138.88  5020.9  146.445084.094150.59585346.241 148.8815817.354151.4511
5954.173149.00776272.641148.50376413.513150.26876727.446148.6456  7560.8  156.28
#Mann= 8 ,-1 , 0
   700.5     .99       0 1294.57     .04       0 4179.44     .04       0
  4701.2     .01       0  4911.5     .04       0  4981.1    .055       0
  5020.9     .04       05084.094     .12       0
#XS Ineff= 1 ,-1
  4179.4  4911.5     149
Permanent Ineff=
       T
#Block Obstruct= 2 ,-1
    4660    4911  143.58    1230    1380   149.5
Bank Sta=4981.1,5020.9
XS Rating Curve= 0 ,0
Exp/Cntr=0.3,0.1