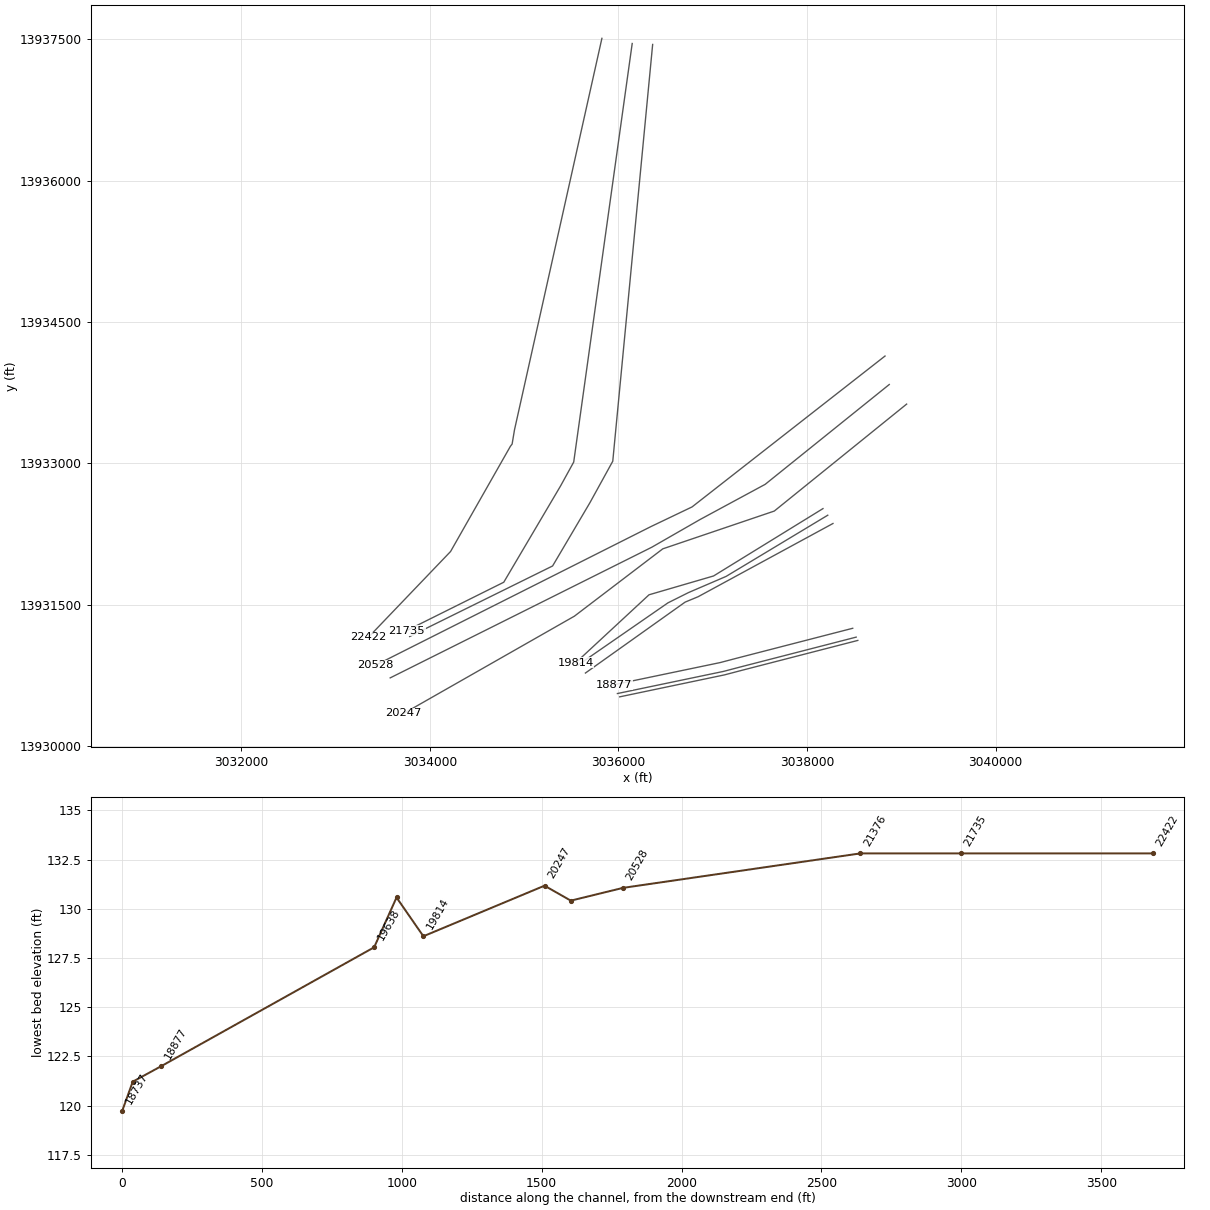
HEC-RAS study K142-00-00.prj: K142-00-00

--- K142-00-00.g01 (geometry) --- (continued)

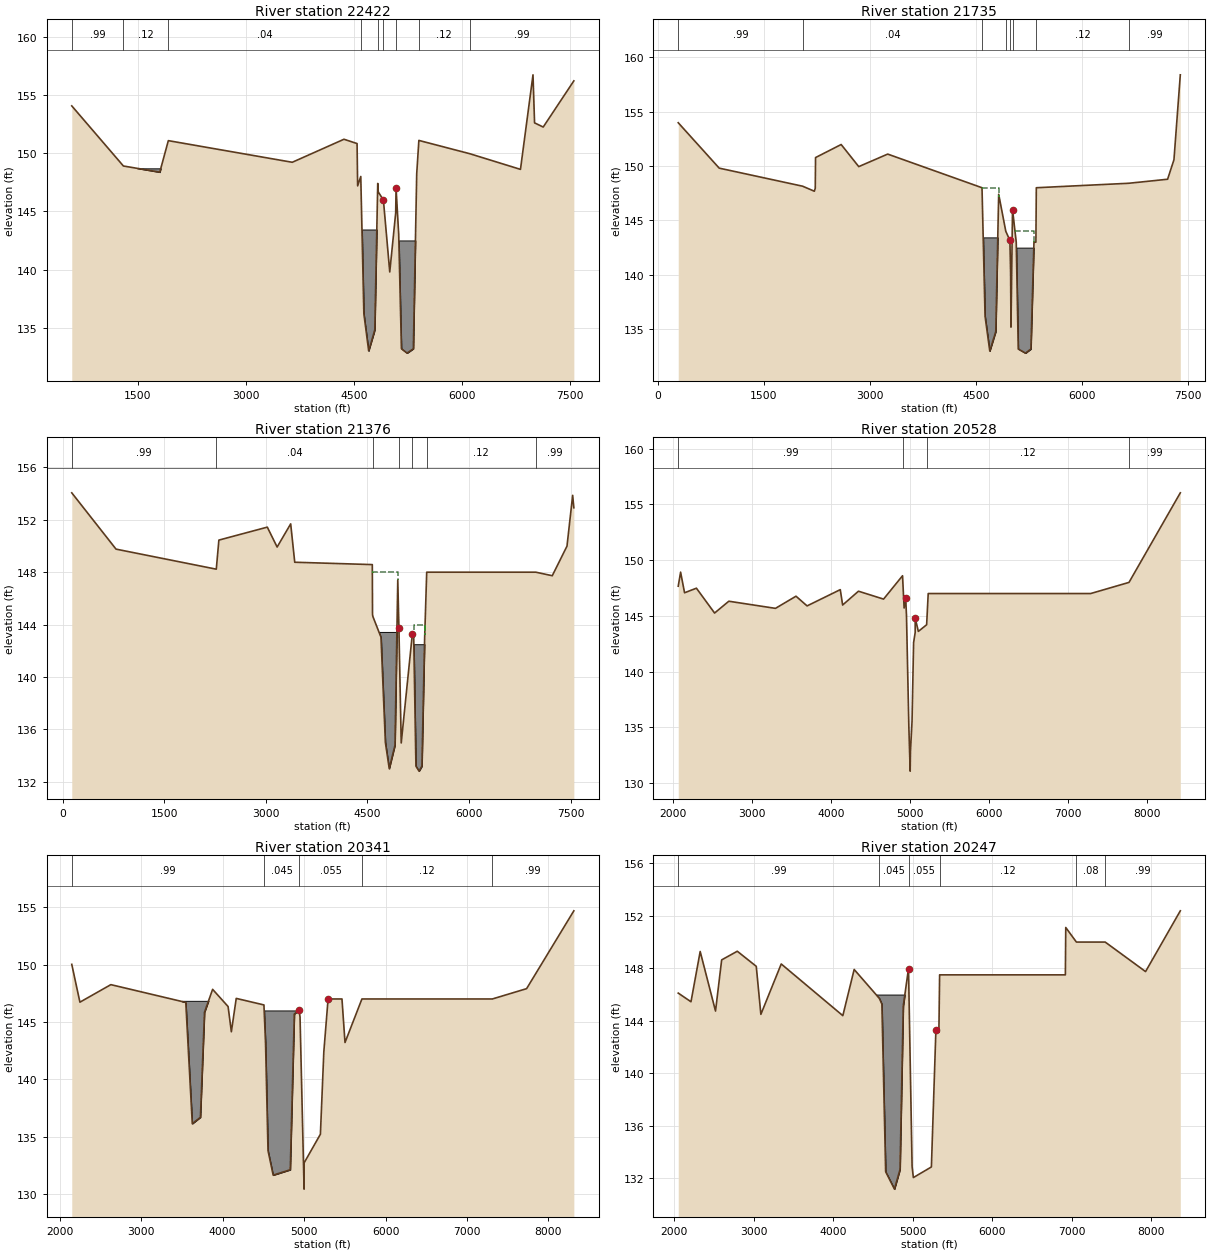
Type RM Length L Ch R = 1 ,22422   ,804.44,687,665.1
BEGIN DESCRIPTION:
New C/S
pond B blocked at 143.31 (CI)
END DESCRIPTION:
XS GIS Cut Line= 6
 3035825.595524313937508.0588804 3034898.715488313933356.7837183
 3034873.462257913933205.3952416 3034854.859604913933181.1895813
 3034220.713563413932065.9690428 3033349.759924813931156.6595097
#Sta/Elev= 30
  579.58  154.07 1297.39   148.9 1803.05  148.37  1921.9  151.08 3644.79  149.22
 4363.73   151.2 4545.71  150.83  4553.5  147.19 4597.07     148 4640.07   136.2
 4707.07     133 4792.07   134.8 4833.07   147.4 4840.46  146.67  4911.7  145.97
    5000  139.79 5082.54  144.86 5087.52     147 5124.58     143 5162.08  133.19
  5240.8  132.81 5328.31  133.19 5374.73  148.23 5404.76   151.1 6110.55  149.96
 6817.13  148.61 6991.33  156.74 7013.02  152.61 7133.37  152.25 7559.12  156.22
#Mann= 9 ,-1 , 0
  579.58     .99       0 1297.39     .12       0  1921.9     .04       0
 4597.07     .01       0 4840.46     .04       0  4911.7    .055       0
 5087.52    .055       0 5404.76     .12       0 6110.55     .99       0
#XS Ineff= 2 ,-1
    4597    4831     146    5102    5373     144
Permanent Ineff=
       T       T
#Block Obstruct= 3 ,-1
 5087.52    5450   142.5 4597.07 4833.07  143.44    1225    1820   148.7
Bank Sta=4911.7,5087.52
XS Rating Curve= 0 ,0
Exp/Cntr=0.3,0.1

Type RM Length L Ch R = 1 ,21735   ,354.03,359,285.98
BEGIN DESCRIPTION:
Cross Section K142-00-00-X09A,
Prop Wildwood FP fill to 149 & pond B blocked at 143.17 (CI)
END DESCRIPTION:
XS GIS Cut Line= 5
 3036146.880812213937453.4638265       3035526.6     13933014.36
      3035387.85     13932762.33      3034784.88     13931740.13
  3033755.36966113931227.5806579
#Sta/Elev= 30
   288.4  153.97   868.4   149.8  2049.4  148.14 2215.27  147.68 2228.26  147.95
 2232.26  150.77 2595.02  151.97 2843.86  149.94 3253.72  151.09  4588.9     148
  4631.9   136.2  4698.9     133  4783.9   134.8  4824.9   147.4  4925.5     144
  4983.5  143.17  4993.6  140.23  4998.9   135.2  5020.8     146 5073.38     143
 5101.85  133.19 5203.82  132.81 5281.23  133.19 5324.34     143  5351.7     143
 5357.69     148  6666.1  148.41  7216.1  148.78  7306.1  150.57  7396.1  158.37
#Mann= 8 ,-1 , 0
   288.4     .99       0  2049.4     .04       0  4588.9     .01       0
  4925.5     .04       0  4983.5    .055       0  5020.8    .055       0
 5357.69     .12       0  6666.1     .99       0
#XS Ineff= 2 ,-1
  4588.9    4824     148    5050    5326     144
Permanent Ineff=
       T       T
#Block Obstruct= 2 ,-1
    4587    4825  143.44  5020.8    5354   142.5
Bank Sta=4983.5,5020.8
XS Rating Curve= 0 ,0
Exp/Cntr=0.3,0.1

Type RM Length L Ch R = 1 ,21376   ,836.27,848,675.52
BEGIN DESCRIPTION:
New C/S
END DESCRIPTION:
XS GIS Cut Line= 5
 3036363.748975513937443.1187215 3035940.782957913933023.5681774
 3035699.332981513932584.9686609 3035302.6992604 13931912.568759
 3033786.868302513931164.4715019
#Sta/Elev= 30
  136.68  154.06  790.27  149.76 2270.01  148.23 2308.24  150.45  3023.2  151.44
 3168.19  149.92 3368.18  151.69 3428.18  148.76 4573.11  148.58 4576.42  144.75
  4583.5  144.59  4701.1  143.04  4766.1     135  4823.1     133  4908.1   134.8
  4949.1   147.4 4965.76  143.75    5000  134.96 5164.21  143.29 5184.43     143
 5217.07  133.19 5263.04  132.81 5305.46  133.19 5345.91     143 5376.14     148
 6987.14     148 7229.62  147.73 7447.07  149.99 7530.71  153.87 7548.14  152.92
#Mann= 7 ,-1 , 0
  136.68     .99       0 2270.01     .04       0  4583.5     .01       0
 4965.76    .055       0 5164.21    .055       0 5376.14     .12       0
 6987.14     .99       0
#XS Ineff= 2 ,-1
    4570  4949.1     148    5184    5347     144
Permanent Ineff=
       T       T
#Block Obstruct= 3 ,-1
                            4606    4948  143.44    5165    5350   142.5
Bank Sta=4965.76,5164.21
XS Rating Curve= 0 ,0
Exp/Cntr=0.3,0.1

Type RM Length L Ch R = 1 ,20528   ,183.6,187,208.6
BEGIN DESCRIPTION:
Cross Section K142-00-00_Interpolated - XS3
END DESCRIPTION:
XS GIS Cut Line= 4
        3038828.      13934138.9      3036781.82      13932538.9
      3036344.39      13932329.7      3033424.39      13930859.7
#Sta/Elev= 30
  2065.7  147.66  2095.7  148.92  2145.7  147.07  2295.7  147.48  2525.7  145.25
  2705.7  146.31  3295.7  145.67  3555.7  146.76  3695.7  145.89  4115.7  147.35
  4145.7  145.97  4345.7  147.21  4663.4   146.5  4903.4   148.6  4923.4   145.7
  4943.3   146.6  4953.4     145  4983.4     135    5000  131.06  5003.4   132.8
  5023.4   135.5  5043.4   142.6  5063.3   143.5  5063.4   144.8  5103.4   143.6
  5208.3   144.2 5228.16     147 7283.72     147  7768.3     148  8417.5  156.04
#Mann= 4 ,-1 , 0
  2065.7     .99       0  4903.4    .055       0  5208.3     .12       0
  7768.3     .99       0
Bank Sta=4943.3,5063.4
XS Rating Curve= 0 ,0
Exp/Cntr=0.3,0.1

Type RM Length L Ch R = 1 ,20341   ,95.62,94,87.01
BEGIN DESCRIPTION:
Cross Section K142-00-00_Interpolated - XS2
END DESCRIPTION:
XS GIS Cut Line= 5
        3038873.       13933837.      3037556.86     13932778.15
       3036867.4     13932405.77       3036353.9     13932110.99
      3033580.54     13930725.86
#Sta/Elev= 30
  2147.2  150.02  2247.2  146.72  2627.2  148.25  3547.2   146.7  3627.2  136.12
  3727.2  136.68  3777.2  145.84  3876.9  147.84  4066.9  146.34  4106.9  144.14
  4166.9  147.05  4506.9  146.48  4526.9  143.11  4556.9  133.78  4620.5  131.63
  4830.4   132.1  4880.4   145.7  4940.3     146  4950.4   145.4    5000  130.41
  5000.3   132.7  5200.4   135.2  5242.5   142.4 5294.75     147  5465.2     147
  5502.5   143.2 5710.19     147 7312.04     147  7732.5   147.9  8312.6  154.69
#Mann= 5 ,-1 , 0
  2147.2     .99       0  4506.9    .045       0  4940.3    .055       0
 5710.19     .12       0 7312.04     .99       0
#Block Obstruct= 2 ,-1
    3500    3900  146.84    4500    4900     146
Bank Sta=4940.3,5294.75
XS Rating Curve= 0 ,0
Exp/Cntr=0.3,0.1

Type RM Length L Ch R = 1 ,20247   ,440.48,433,400.79
BEGIN DESCRIPTION:
New C/S
END DESCRIPTION:
XS GIS Cut Line= 5
 3039057.221606913933629.2923597 3037653.5232989 13932494.815626
 3036471.247448213932094.2586844 3035534.130884113931380.3647709
 3033724.675185413930349.3714261
#Sta/Elev= 30
 2050.19  146.11 2210.55  145.45 2326.27  149.28 2519.13  144.74 2596.28  148.64
  2792.8   149.3 3031.43  148.15 3089.43  144.49 3345.41  148.33 4120.05  144.39
 4262.59  147.91    4579  145.71 4611.02  145.28 4658.53   132.5 4769.39  131.17
 4839.51  132.67 4880.25  145.13 4945.97  147.98 4991.12  132.89 5006.95  132.05
 5233.73  132.86  5290.3  143.26 5328.01  143.15 5337.23   147.5 6918.44   147.5
 6923.44  151.11    7057     150 7419.18     150 7926.99  147.75 8363.93  152.38
#Mann= 6 ,-1 , 0
 2050.19     .99       0    4579    .045       0 4945.97    .055       0
 5337.23     .12       0    7057     .08       0 7419.18     .99       0
#Block Obstruct= 1 ,-1
    4513    4924     146
Bank Sta=4945.97,5290.3
XS Rating Curve= 0 ,0
Exp/Cntr=0.3,0.1

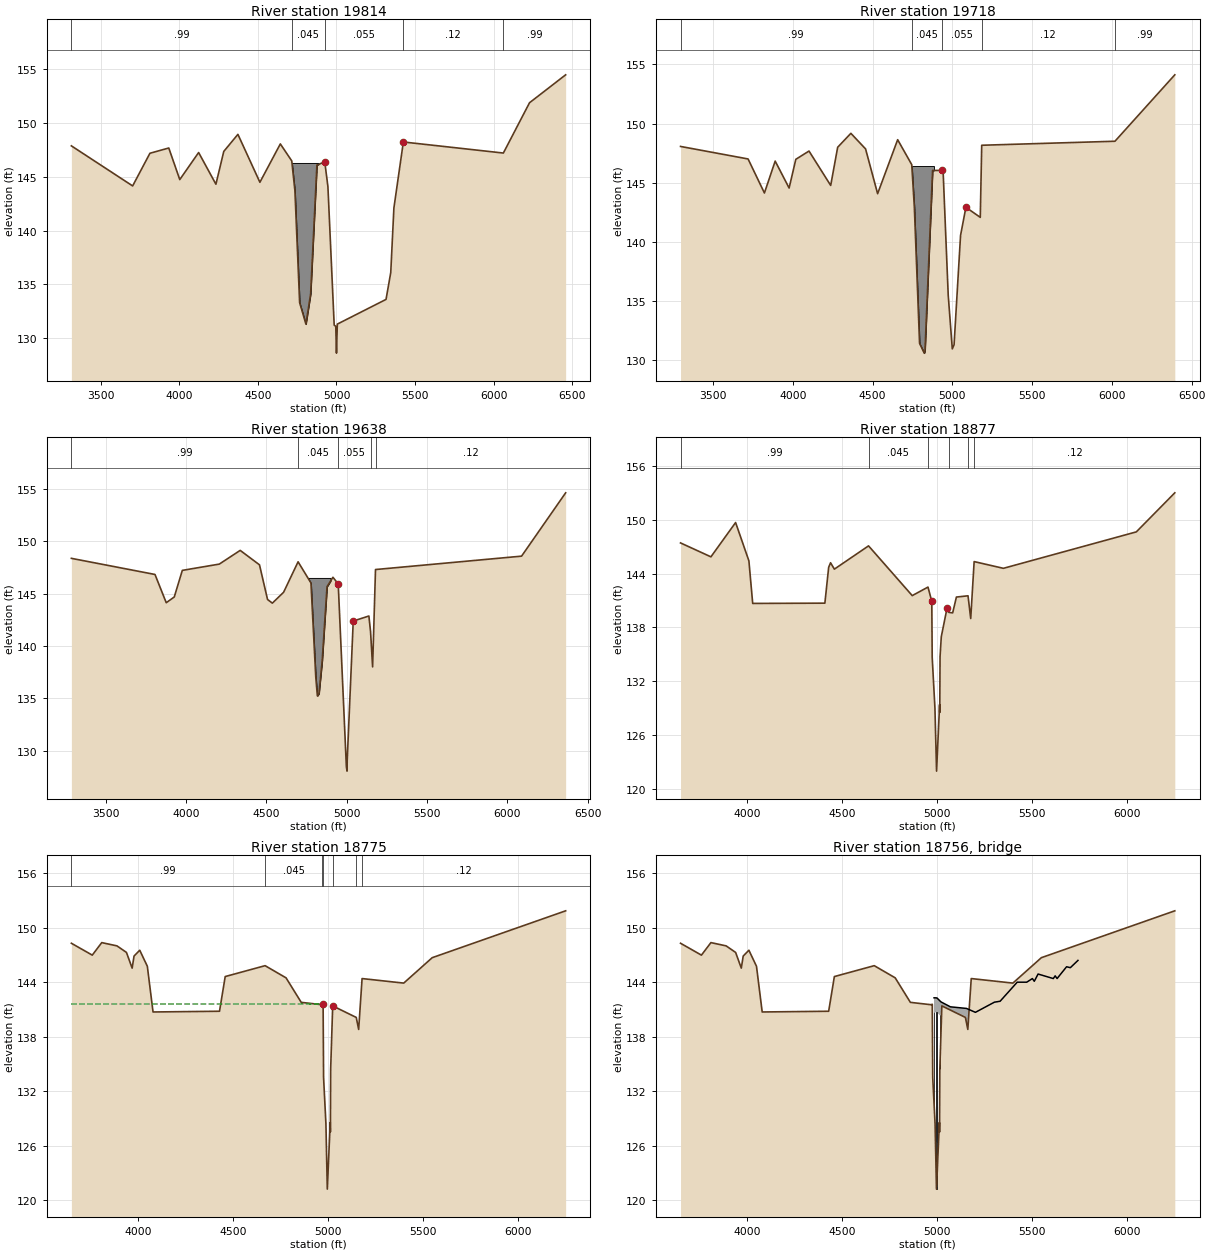
Type RM Length L Ch R = 1 ,19814   ,93.22,96,114.33
BEGIN DESCRIPTION:
Cross Section K142-00-00_Interpolated - XS1
END DESCRIPTION:
XS GIS Cut Line= 4
        3038170.       13932521.      3037010.04     13931806.69
      3036325.37       13931607.     3035547.763    13930886.284
#Sta/Elev= 30
  3312.6  147.89  3702.6  144.16  3812.6   147.2  3932.6  147.69  4002.6  144.75
  4122.6  147.27  4232.6  144.32  4282.6  147.37  4372.6  148.96  4512.6   144.5
  4642.6  148.07 4715.35  146.49  4735.5   143.7  4765.5   133.3  4805.5   131.3
  4835.5   134.1  4875.5   146.1  4925.4   146.4  4945.5   144.1  4985.5   131.2
  4995.5   131.1    5000   128.6  5005.4   131.3  5315.5   133.6  5345.5   136.1
  5365.5   142.1 5425.67  148.25 6062.27  147.22  6228.7   151.9  6458.7   154.5
#Mann= 5 ,-1 , 0
  3312.6     .99       0 4715.35    .045       0  4925.4    .055       0
 5425.67     .12       0 6062.27     .99       0
#Block Obstruct= 3 ,-1
                                                  4715.8  4885.5   146.3
Bank Sta=4925.4,5425.67
XS Rating Curve= 0 ,0
Exp/Cntr=0.3,0.1

Type RM Length L Ch R = 1 ,19718   ,77.68,80,95.27
BEGIN DESCRIPTION:
New C/S
END DESCRIPTION:
XS GIS Cut Line= 5
 3038220.712453213932450.7940605 3037142.008245813931801.6047421
 3036743.497559913931630.2533788 3036526.247010113931521.5688848
 3035570.841440613930860.5921884
#Sta/Elev= 30
 3296.98  148.06 3720.32     147 3822.69  144.12 3890.07  146.82 3977.46  144.54
 4019.42  146.97 4102.06  147.67    4238  144.76 4281.72  147.99 4364.48  149.17
 4456.59  147.85 4532.05  144.06 4657.68  148.63 4745.92  146.52 4762.25  142.91
 4794.91   131.4 4824.08  130.57 4828.95  130.78 4876.55  146.03 4934.68  146.03
 4943.13  145.75 4974.51  135.47    5000  130.93 5011.18  131.28 5051.79  140.53
 5085.31  142.91 5175.37  142.06 5184.44  148.16 6019.44   148.5 6394.44  154.12
#Mann= 5 ,-1 , 0
 3296.98     .99       0 4745.92    .045       0 4934.68    .055       0
 5184.44     .12       0 6019.44     .99       0
#Block Obstruct= 1 ,-1
    4745    4885   146.4
Bank Sta=4934.68,5085.31
XS Rating Curve= 0 ,0
Exp/Cntr=0.3,0.1

Type RM Length L Ch R = 1 ,19638   ,760.3,761,767.6
BEGIN DESCRIPTION:
Cross Section K142-00-00-X9
END DESCRIPTION:
XS GIS Cut Line= 4
        3038276.       13932363.      3036846.55     13931586.74
      3036708.12     13931529.28      3035650.81      13930777.2
#Sta/Elev= 30
  3287.6  148.37  3807.6  146.83  3877.6  144.13  3927.6  144.68  3977.6  147.22
  4207.6  147.82  4337.6  149.13  4457.6  147.75  4507.6  144.44  4537.6  144.09
  4607.6  145.13  4697.6  148.04  4777.6  146.02  4807.6  137.03  4817.6  135.23
  4827.6  135.45  4847.6  138.58  4877.6  145.66  4914.4  146.56  4947.2  145.93
  4997.9  128.47  5002.1  128.04  5003.2  129.08  5040.6  142.38    5138  142.86
  5148.4  141.35 5161.11     138 5179.11   147.3  6087.6  148.58  6361.7  154.63
#Mann= 5 ,-1 , 0
  3287.6     .99       0  4697.6    .045       0  4947.2    .055       0
  5148.4    .035       0 5179.11     .12       0
#Block Obstruct= 2 ,-1
    4760    4900   146.5    5605    5955     146
Bank Sta=4947.2,5040.6
XS Rating Curve= 0 ,0
Exp/Cntr=0.3,0.1

Type RM Length L Ch R = 1 ,18877   ,99.7,102,101.6
BEGIN DESCRIPTION:
K142-00-00-S0-7_ABANDONED WOOD BR-US - XS4
END DESCRIPTION:
XS GIS Cut Line= 4
       3038485.3      13931251.8      3037262.36     13930936.16
      3037078.98     13930887.98      3035953.26     13930653.18
#Sta/Elev= 30
  3648.5  147.42  3808.5  145.87  3938.5  149.69  4008.5  145.42  4028.5  140.68
  4408.5  140.71  4428.5   144.7  4438.5  145.21  4458.5   144.5  4638.5  147.09
  4868.5  141.55  4951.5   142.5  4971.5   140.9 4973.66  134.68 4988.07  129.02
 4996.62     122 5012.65  129.41 5013.48  128.54 5015.04  134.76  5021.5  136.97
  5051.5  140.12  5061.5  139.68  5081.5  139.63  5101.1  141.39 5162.27  141.53
  5176.5     139  5194.5  145.34  5348.5  144.59  6048.5  148.65  6251.1     153
#Mann= 6 ,-1 , 0
  3648.5     .99       0  4638.5    .045       0  4951.5     .06       0
  5061.5      .1       0 5162.27    .035       0  5194.5     .12       0
#XS Ineff= 2 , 0
       0  4873.8   141.6  5124.3       0   141.1
Permanent Ineff=
       F       F
Bank Sta=4971.5,5051.5
XS Rating Curve= 0 ,0
Exp/Cntr=0.5,0.3

Type RM Length L Ch R = 1 ,18775   ,37.8,38,38.5
BEGIN DESCRIPTION:
K142-00-00-S0-7_ABANDONED WOOD BR-US - XS3
END DESCRIPTION:
XS GIS Cut Line= 4
        3038522.       13931158.      3037299.25     13930842.84
      3037115.87     13930794.66      3035990.15      13930559.8
#Sta/Elev= 30
  3648.3  148.29  3758.3  146.98  3808.3  148.36  3888.3     148  3938.3  147.28
  3968.3  145.55  3978.3  146.88  4008.3  147.52  4048.3  145.75  4078.3  140.72
  4428.3   140.8  4458.3  144.62  4668.3  145.82  4778.6  144.48  4858.6  141.78
  4967.1  141.52  4973.8  141.57  4976.3  133.49  4988.6  128.42  4995.9  121.21
  5011.3  128.54  5012.1   127.5  5013.6  134.44  5024.3  141.39  5148.3  140.12
 5161.02   138.8 5179.02   144.4  5398.3   143.9  5548.3   146.7  6250.9  151.86
#Mann= 7 ,-1 , 0
  3648.3     .99       0  4668.3    .045       0  4967.1     .08       0
  4973.8     .08       0  5024.3      .1       0  5148.3    .035       0
 5179.02     .12       0
#XS Ineff= 2 , 0
       0  4973.8   141.6  5024.3       0   141.1
Permanent Ineff=
       F       F
Bank Sta=4973.8,5024.3
XS Rating Curve= 0 ,0
Exp/Cntr=0.5,0.3

Type RM Length L Ch R = 3 ,18756   ,,,
BEGIN DESCRIPTION:
1720' D/S OF SHADY GLEN
Ref. PIC K142-00-00S7P1.JPG: TOR is washed out.
Structure ID: K142-00-00-S0-7
END DESCRIPTION:
Bridge Culvert--1,0,-1,-1, 0
Deck Dist Width WeirC Skew NumUp NumDn MinLoCord MaxHiCord MaxSubmerge Is_Ogee
10,14,2.6,0, 31, 31, , , 0.95, 0, ,,,
  4983.1  4983.8  4986.4  4988.6  4989.4  4995.9  4998.2  5011.3  5012.1  5013.6
  5019.2 5022.39 5022.49  5022.6  5024.3  5068.8  5154.3    5201    5301    5331
    5421    5471    5501    5511    5531    5611    5621    5631    5681    5701
    5741
  142.28  142.28  142.28  142.28  142.28  142.27  142.27     142  141.99  141.95
  141.84   141.8   141.8   141.8  141.78  141.29  141.11  140.68   141.8   141.9
     144     144   144.4   144.1   144.9   144.4   144.7   144.4   145.7   145.6
   146.4
  140.68  140.68  140.68  140.68  140.68  140.67  140.67   140.4  140.39  140.35
  140.24   140.2  140.21  140.28  141.31   138.5   138.5  140.68   141.8   141.9
     144     144   144.4   144.1   144.9   144.4   144.7   144.4   145.7   145.6
   146.4
  4983.1  4983.8  4986.4  4988.6  4989.4  4995.9  4998.2  5011.3  5012.1  5013.6
  5019.2 5022.39 5022.49  5022.6  5024.3  5068.8  5154.3    5201    5301    5331
    5421    5471    5501    5511    5531    5611    5621    5631    5681    5701
    5741
  142.28  142.28  142.28  142.28  142.28  142.27  142.27     142  141.99  141.95
  141.84   141.8   141.8   141.8  141.78  141.29  141.11  140.68   141.8   141.9
     144     144   144.4   144.1   144.9   144.4   144.7   144.4   145.7   145.6
   146.4
  139.23  139.23  139.23  139.23  139.23  139.22  139.22  138.95  138.94   138.9
  138.79  138.75  138.76  138.83  139.86   138.5   138.5  139.23  140.35  140.45
  142.55  142.55  142.95  142.65  143.45  142.95  143.25  142.95  144.25  144.15
  144.95
Pier Skew, UpSta & Num, DnSta & Num=  ,4983.8, 2 ,4983.8, 2 , 0 , 0 , 0 ,,
     1.1     1.1
  129.13  141.68
     1.1     1.1
  127.68  140.23
Pier Skew, UpSta & Num, DnSta & Num=  ,4995.9, 2 ,4995.9, 2 , 0 , 0 , 0 ,,
     1.1     1.1
  120.39  141.67
     1.1     1.1
  118.94  140.22
Pier Skew, UpSta & Num, DnSta & Num=  ,5013.6, 2 ,5013.6, 2 , 0 , 0 , 0 ,,
     1.1     1.1
  130.82  141.36
     1.1     1.1
  129.37  139.91
BR Coef= 1 , 1 , 1 ,1.05, 0 ,,,0.8,0,1.2,0,
WSPro=,,,, 1 ,,,, 0 ,,,, 0 ,,,,-1 ,-1 ,-1 , 0 , 0 , 0 , 0 , 0
BC Design=,, 0 ,, 0 ,,,,,,
BC HTab HWMax=151.86
BC Use User HTab Curves=0
BC User HTab FreeFlow(D)= 0

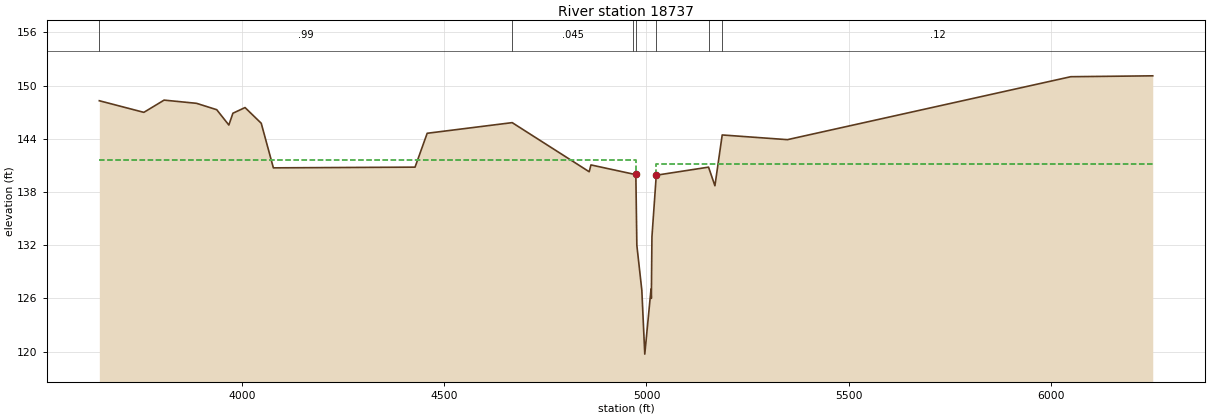
Type RM Length L Ch R = 1 ,18737   ,101,101,101.7
BEGIN DESCRIPTION:
K142-00-00S0-7_ABANDONED WOOD BR-DS - XS2
END DESCRIPTION:
XS GIS Cut Line= 4
       3038539.5       13931123.      3037312.82     13930806.77
      3037124.84     13930757.38     3036014.406    13930524.691
#Sta/Elev= 30
  3648.3  148.29  3758.3  146.98  3808.3  148.36  3888.3     148  3938.3  147.28
  3968.3  145.55  3978.3  146.88  4008.3  147.52  4048.3  145.75  4078.3  140.72
  4428.3   140.8  4458.3  144.62  4668.3  145.82  4858.6  140.28  4862.9  141.05
  4967.1  140.02  4973.8  140.07  4976.3  131.99  4988.6  126.92  4995.9  119.71
  5011.3  127.04  5012.1     126  5013.6  132.94  5024.3  139.89 5153.45   140.8
  5169.2   138.7  5187.2  144.43  5348.3   143.9  6048.3     151  6250.9   151.1
#Mann= 7 ,-1 , 0
  3648.3     .99       0  4668.3    .045       0  4967.1     .08       0
  4973.8    .076       0  5024.3      .1       0 5153.45    .035       0
  5187.2     .12       0
#XS Ineff= 2 , 0
       0  4973.8   141.6  5024.3       0   141.1
Permanent Ineff=
       F       F
Bank Sta=4973.8,5024.3
XS Rating Curve= 0 ,0
Exp/Cntr=0.5,0.3