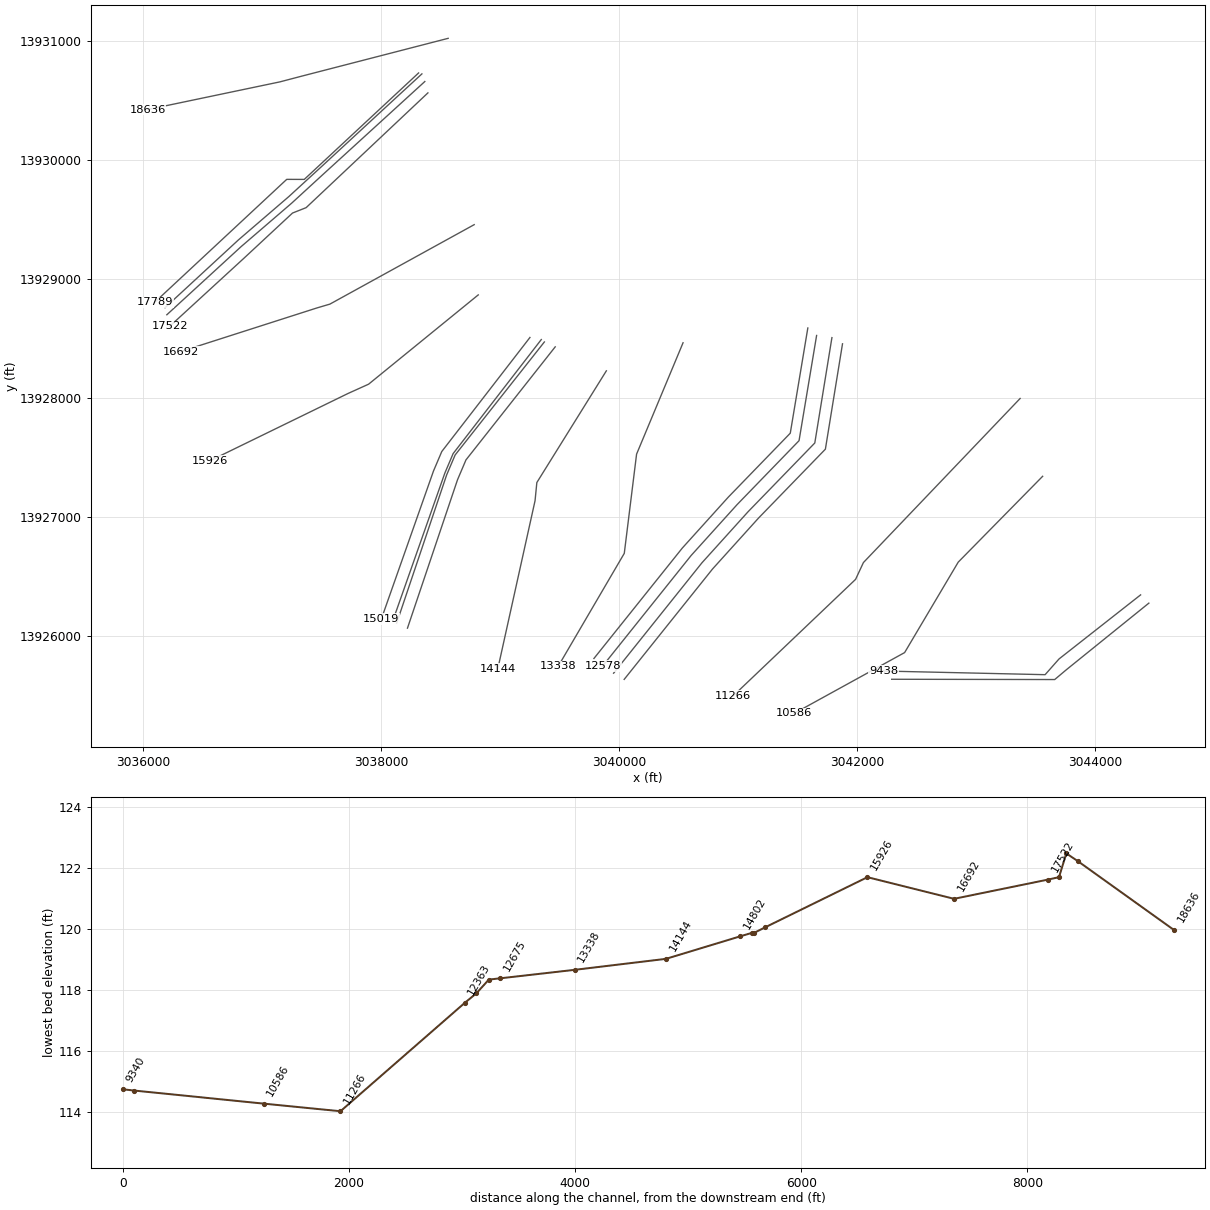
HEC-RAS study K142-00-00.prj: K142-00-00

--- K142-00-00.g01 (geometry) --- (continued)

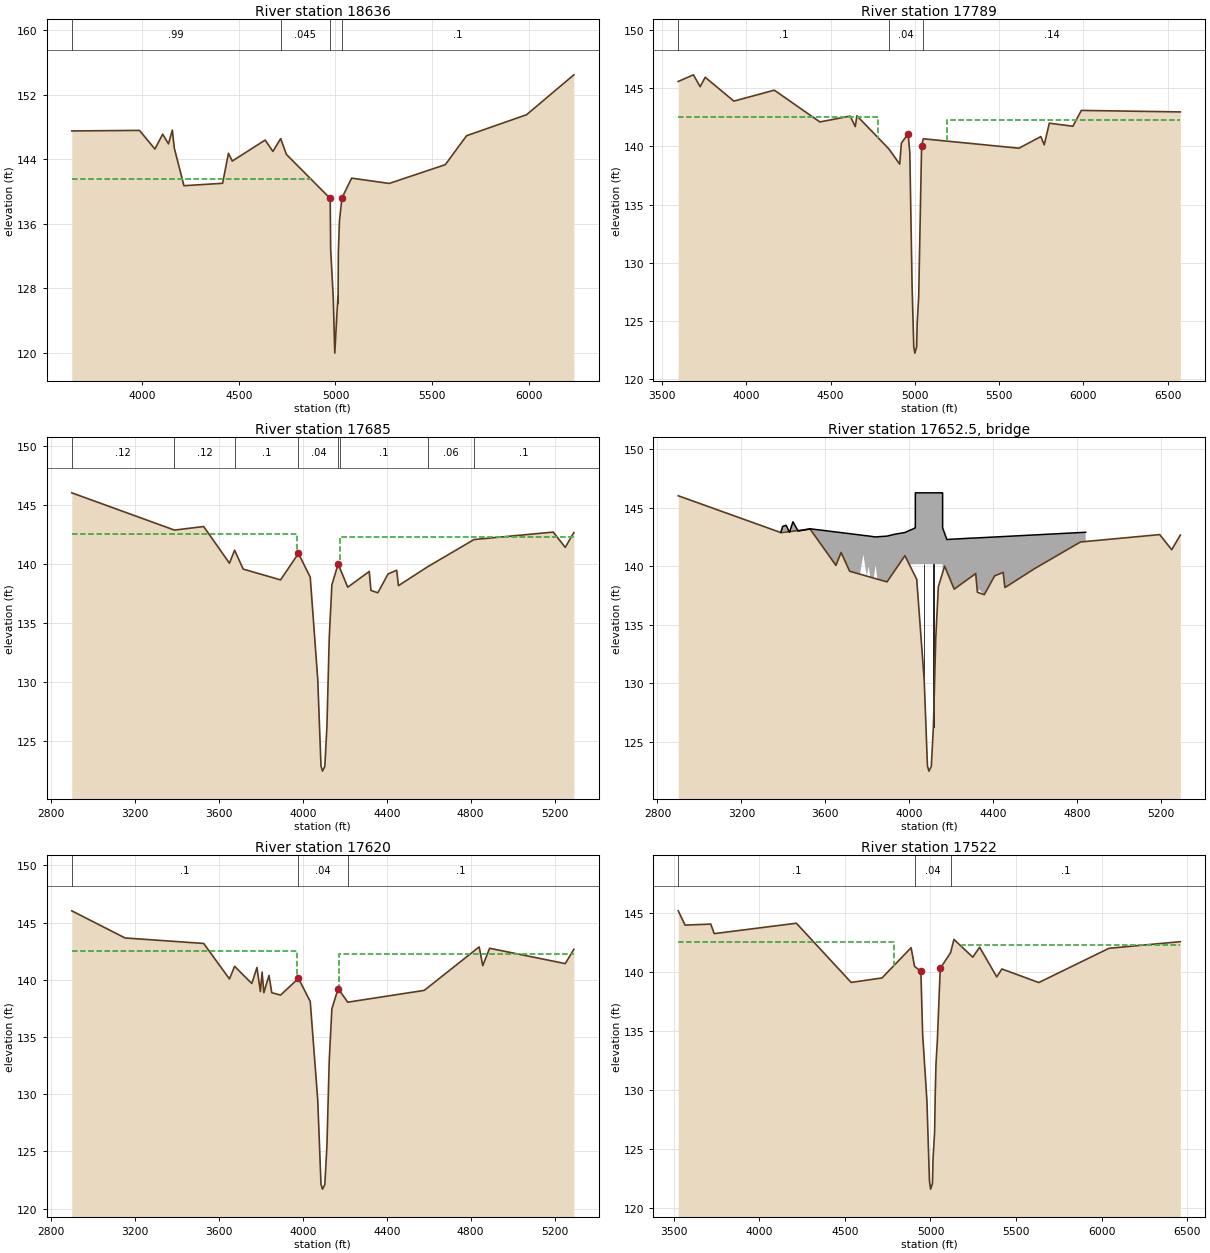
Type RM Length L Ch R = 1 ,18636   ,848.6,847,841.4
BEGIN DESCRIPTION:
K142-00-00S0-7_ABANDONED WOOD BR-DS - XS1
END DESCRIPTION:
XS GIS Cut Line= 4
      3038563.42      13931026.1      3037336.69     13930709.12
      3037148.71     13930659.73      3036038.28     13930427.04
#Sta/Elev= 30
  3636.4  147.53  3986.4   147.6  4066.4  145.29  4106.4  147.13  4136.4  145.93
  4156.4  147.64  4166.4  145.42  4216.4  140.74  4416.4  141.04  4446.4  144.76
  4466.4   143.8  4636.4   146.4  4676.4  144.99  4716.4  146.58  4746.4  144.62
 4972.66  139.16 4975.04  132.88  4988.4  126.86 4996.33  119.98  5012.4     127
 5013.23  126.12 5014.79  132.54 5020.64  136.43  5033.4  139.22  5083.4  141.68
  5277.8  141.02  5567.8  143.35  5677.8  146.94  5987.8  149.54  6232.4  154.49
#Mann= 4 ,-1 , 0
  3636.4     .99       0  4716.4    .045       0 4972.66     .06       0
  5033.4      .1       0
#XS Ineff= 2 , 0
       0  4873.8   141.6  5124.3       0   141.1
Permanent Ineff=
       F       F
Bank Sta=4972.66,5033.4
XS Rating Curve= 0 ,0
Exp/Cntr=0.3,0.1

Type RM Length L Ch R = 1 ,17789   ,87.9,104,123.2
BEGIN DESCRIPTION:
K142-00-00-S6_SPRING CYPRESS RD - US - XS4
END DESCRIPTION:
XS GIS Cut Line= 4
      3038315.06       13930735.      3037354.04     13929839.46
      3037206.55     13929839.82       3036096.8     13928805.41
#Sta/Elev= 30
  3596.3  145.59  3686.3  146.16  3726.3  145.14  3756.3  145.95  3926.3   143.9
  4166.3  144.84  4436.3  142.11  4616.3  142.61  4646.3  141.71  4656.3  142.64
  4846.3  139.78  4909.9  138.48  4919.9  140.29  4959.9  141.09  4969.9  139.49
 4983.52  127.99  4993.5  122.76    5000  122.23 5010.56  122.78 5013.65   124.8
 5022.74  127.11  5039.9  140.08  5049.9  140.66  5617.4  139.85  5747.4  140.85
  5767.4  140.14  5797.4     142  5937.4  141.74  5987.4   143.1  6574.5  142.97
#Mann= 3 ,-1 , 0
  3596.3      .1       0  4846.3     .04       0  5049.9     .14       0
#XS Ineff= 2 , 0
       0    4783   142.5    5189       0  142.28
Permanent Ineff=
       F       F
Bank Sta=4959.9,5039.9
XS Rating Curve= 0 ,0
Exp/Cntr=0.5,0.3

Type RM Length L Ch R = 1 ,17685   ,64,65,69.9
BEGIN DESCRIPTION:
K142-00-00-S6_SPRING CYPRESS RD - US - XS3
END DESCRIPTION:
XS GIS Cut Line= 6
      3038342.86      13930727.1      3038065.82     13930471.61
      3037478.44     13929928.23      3037225.08      13929695.7
       3036800.7     13929330.59      3036183.72      13928760.5
#Sta/Elev= 30
2898.897  146.023388.341  142.873527.595  143.173650.468  140.073675.044  141.17
    3716  139.573894.003  138.663979.441   140.94035.552  138.884071.186  130.28
 4086.75  122.934093.794  122.494105.017  122.894114.928  126.244126.151  133.78
4138.602  138.244168.501  140.014179.314  139.54 4214.21  138.044316.686  139.37
4324.877  137.774357.644  137.574406.792  139.17 4447.75  139.474455.941  138.17
4595.197  139.774816.205  142.075193.588   142.7 5250.93  141.415291.886  142.66
#Mann= 8 ,-1 , 0
2898.897     .12       03388.341     .12       03675.044      .1       0
3979.441     .04       04168.501    .045       04179.314      .1       0
4595.197     .06       04816.205      .1       0
#XS Ineff= 2 , 0
       03971.249   142.54176.691       0  142.28
Permanent Ineff=
       F       F
Bank Sta=3979.441,4168.501
XS Rating Curve= 0 ,0
Skew Angle= 35
Exp/Cntr=0.5,0.3

Type RM Length L Ch R = 3 ,17652.5 ,,,
BEGIN DESCRIPTION:
SPRING CYPRESS ROAD
Structure ID: K142-00-00-S6
END DESCRIPTION:
Bridge Culvert--1,0,-1,-1, 0
Deck Dist Width WeirC Skew NumUp NumDn MinLoCord MaxHiCord MaxSubmerge Is_Ogee
10,41,2.6,35, 44, 43, , , 0.95, 0, ,,,
3388.3413396.5323412.9153429.298 3445.683470.2563527.5953552.1713576.7453642.278
3666.8513675.044    3716 3765.153781.5333789.7253797.9173806.107  3814.33830.683
3838.8733840.6773847.0663852.1453894.0853923.7383936.3523979.2774000.5344028.835
4028.9914029.0814158.7454158.8354158.9994159.0894179.314 4214.214308.4944316.686
4324.8774333.0694357.6444840.779
   142.9   143.4   143.5   142.9   143.8     143   143.2  143.14  143.09  142.94
  142.89  142.87  142.78  142.67  142.63  142.61   142.6  142.58  142.56  142.52
   142.5   142.5  142.51  142.52  142.57   142.7  142.75  142.88  143.05  143.27
  143.27  146.27  146.27  146.27  146.27  143.27  142.28  142.32  142.41  142.41
  142.42  142.43  142.45   142.9
     142     143     143     142     142     142     143     141     141     140
     140     141     139     139     141     140     138     140     138     139
     140     140     139     138     138     139     139     140     140  140.17
  140.17  140.17  140.17     139     139     139     139     138     138     139
     137     138     137     137
3388.3413396.5323412.9153429.298 3445.683470.2563527.5953552.1713576.7453642.278
3666.8513675.044    3716 3765.153781.5333789.7253797.9173806.107  3814.33830.683
3838.8733840.6773847.0663852.1453894.0853923.7383979.4413993.3664000.5344028.991
4029.0814158.7454158.8354158.9994159.0894179.314 4214.214308.4944316.6864324.877
4333.0694357.6444840.779
   142.9   143.4   143.5   142.9   143.8     143   143.2  143.14  143.09  142.94
  142.89  142.87  142.78  142.67  142.63  142.61   142.6  142.58  142.56  142.52
   142.5   142.5  142.51  142.52  142.57   142.7  142.88  142.99  143.05  143.27
  146.27  146.27  146.27  146.27  143.27  142.28  142.32  142.41  142.41  142.42
  142.43  142.45   142.9
     142     143     143     142     142     142     143     141     141     140
     140     141     139     139     141     140     138     140     138     139
     140     140     139     138     138     139     139     139  140.17  140.17
  140.17  140.17     139     139     139     139     138     138     139     137
     138     137     137
Pier Skew, UpSta & Num, DnSta & Num=  ,4071.186, 2 ,4071.186, 2 , 0 , 0 , 0 ,,
     1.4     1.4
  129.09  141.17
     1.4     1.4
  128.29  140.37
Pier Skew, UpSta & Num, DnSta & Num=  ,4114.928, 2 ,4114.928, 2 , 0 , 0 , 0 ,,
     1.4     1.4
  125.17  141.17
     1.4     1.4
  124.37  140.37
BR Coef= 1 , 1 , 1 ,1.25, 0 ,,,0.8,0,2,0,
WSPro=,,,, 1 ,,,, 0 ,,,, 0 ,,,,-1 ,-1 ,-1 , 0 , 0 , 0 , 0 , 0
BR D #Sta/Elev= 173
  2898.9  146.02 2915.28  146.18 2964.43  145.24    2989  145.69 3005.39   145.1
 3062.73  144.92 3070.92  144.57 3120.07  144.03 3144.64  144.17 3152.83  143.65
 3161.03  144.03 3169.22  143.75 3177.41  144.36 3201.98  144.16 3208.05  143.89
 3216.24  144.17 3224.43  143.72 3240.81  144.08 3257.19  143.91 3265.39  144.31
 3322.73  143.85 3339.11  144.23 3371.88  143.89 3388.34  142.87 3396.53  143.37
 3412.92  143.47  3429.3  142.87 3445.68  143.77 3470.26  142.97 3527.48  143.17
  3527.6  143.17 3552.17  141.87 3576.75  141.87 3642.28  140.77 3650.47  140.07
 3658.66  140.87 3666.85  140.07 3675.04  141.17    3716  139.57 3732.38  139.87
 3740.58  139.57 3748.77  139.97 3756.96  139.67 3765.15  139.77 3773.34  140.77
 3781.53  141.07 3789.73  140.47 3797.92  138.97 3806.11  140.67  3814.3  138.87
 3830.68  139.07 3838.87  140.37 3840.68  140.15 3847.07  139.37 3852.15  138.87
 3868.53  138.79    3894  138.66 3894.09  138.66 3923.74  139.46 3935.29  139.77
 3936.35   139.8 3979.28  140.12 3979.44  140.12 3993.29  139.62 3993.37  139.62
 4000.53  139.36 4028.84  138.34 4028.99  138.34 4029.08  138.33 4029.17  138.33
 4035.55   138.1 4044.81  135.63 4053.98  133.42 4066.52  130.13 4071.19   129.5
 4075.94  127.71 4083.47  124.07 4085.28  122.85 4086.75  122.15 4093.79  121.71
 4105.02  122.11 4106.25  122.86 4108.29  124.28 4114.93  125.46 4117.96  126.65
  4121.4  130.02 4126.15     133 4134.42   135.1  4138.6  137.46 4157.43  138.84
 4158.75  138.94 4158.84  138.94 4158.91  138.95    4159  138.96 4159.09  138.96
 4160.56  139.07  4168.5  139.23 4179.31  139.54 4214.21  138.04 4215.44  138.05
 4255.82  138.31 4298.17  138.16 4298.42  138.16 4308.49  138.37 4316.69  139.37
 4324.88  137.77 4333.07  138.77 4357.64  137.57 4365.84  137.97 4374.03  138.77
 4382.22  138.07 4390.41  138.97 4406.79  139.17 4414.98  138.87 4423.18  138.17
 4431.37  139.37 4439.56  138.67 4447.75  139.47 4455.94  138.17 4464.13  139.17
 4472.33  138.77  4496.9  139.27 4513.28  138.77 4529.67  139.47 4537.86  139.57
 4546.05  139.07 4554.24  139.47 4570.62  139.07 4578.81  139.07  4595.2  139.77
 4603.23  139.47 4619.61  139.87 4635.99  139.67 4652.37  140.67 4660.57  140.67
 4693.33  140.87 4816.21  142.07  4840.7  142.87 4840.78  142.87 4849.54  142.41
 4857.74  141.23  4890.5  142.75 4915.08     142 4923.27  142.57 4956.03  141.61
 4964.23  142.06 4972.42   141.7 4980.61  142.25  4988.8  141.55 4996.99  142.34
 5013.38  142.67 5021.57  142.05 5037.95  142.67 5078.91  141.75 5095.29  142.26
 5103.48  141.91 5119.86   142.1 5128.06   142.6 5136.25  142.02 5152.63  142.54
 5160.82  142.37 5169.01  141.78 5177.21  141.83 5193.59   142.7 5209.97   141.5
 5226.35  141.58 5234.55  142.27 5242.74  142.28 5250.93  141.41 5259.12  142.55
 5267.31  141.86  5275.5  142.75 5291.89  142.66
BR D #Mann= 3
  2898.9      .1 3979.44     .04 4214.21      .1
BR D Banks=3979.44,4179.31
BC Design=,, 0 ,, 0 ,,,,,,
BC HTab HWMax=146.18
BC Use User HTab Curves=0
BC User HTab FreeFlow(D)= 0

Type RM Length L Ch R = 1 ,17620   ,107.1,98,86.9
BEGIN DESCRIPTION:
K142-00-00-S6_SPRING CYPRESS RD - DS - XS2
END DESCRIPTION:
XS GIS Cut Line= 5
      3038367.32      13930662.8      3037502.52     13929873.06
      3037248.87     13929640.27      3036822.66     13929273.58
      3036199.06       13928701.
#Sta/Elev= 30
2898.897  146.023152.833  143.653527.595  143.173650.468  140.073675.044  141.17
3756.959  139.673781.533  141.073797.917  138.973806.107  140.67  3814.3  138.87
3838.873  140.373852.145  138.873894.003  138.663979.441  140.124035.552   138.1
4071.186   129.5 4086.75  122.154093.794  121.714105.017  122.114114.928  125.46
4126.151     1334138.602  137.464168.501  139.23 4214.21  138.044578.814  139.07
4840.696  142.874857.736  141.234890.502  142.75 5250.93  141.415291.886  142.66
#Mann= 3 ,-1 , 0
2898.897      .1       03979.441     .04       0 4214.21      .1       0
#XS Ineff= 2 , 0
       03973.977   142.54173.965       0  142.28
Permanent Ineff=
       F       F
Bank Sta=3979.441,4168.501
XS Rating Curve= 0 ,0
Skew Angle= 35
Exp/Cntr=0.5,0.3

Type RM Length L Ch R = 1 ,17522   ,831.2,830,827.1
BEGIN DESCRIPTION:
K142-00-00-S6_SPRING CYPRESS RD - DS - XS1
END DESCRIPTION:
XS GIS Cut Line= 5
      3038393.37      13930567.3      3037369.63     13929601.91
      3037255.26     13929556.59       3036848.7     13929178.09
       3036225.1     13928605.51
#Sta/Elev= 30
  3527.1  145.18  3567.1  143.97  3717.1  144.06  3737.1  143.25  4217.1  144.13
  4537.1  139.12  4717.1   139.5  4887.1  142.06  4907.1  140.48  4944.2  140.06
 4954.56   134.7 4979.49  129.12 4994.21  122.34 5000.87  121.63 5011.83   122.1
 5015.02  124.17 5024.46   126.5 5027.82  129.54 5032.46  132.24 5040.54  134.25
  5057.3  140.31  5117.3  141.63  5137.3  142.76  5247.3  141.26  5287.3   142.1
  5387.3  139.59  5417.3  140.26  5632.7  139.11  6042.7  142.01  6459.3  142.57
#Mann= 3 ,-1 , 0
  3527.1      .1       0  4907.1     .04       0  5117.3      .1       0
#XS Ineff= 2 , 0
       0    4786   142.5    5186       0  142.28
Permanent Ineff=
       F       F
Bank Sta=4944.2,5057.3
XS Rating Curve= 0 ,0
Exp/Cntr=0.3,0.1

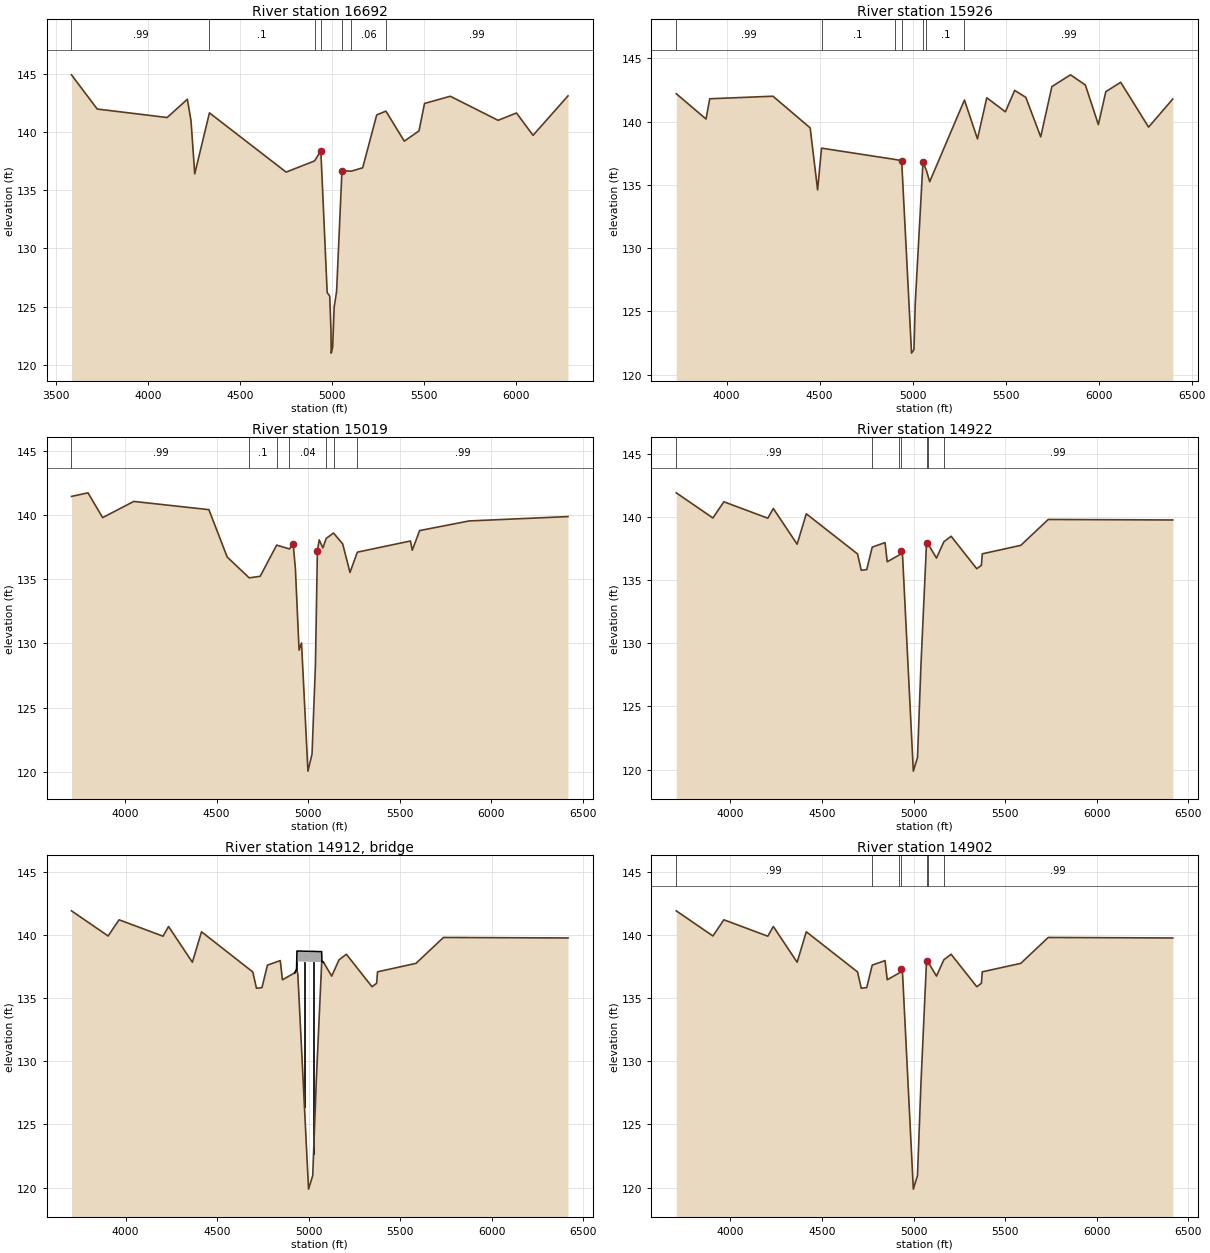
Type RM Length L Ch R = 1 ,16692   ,758.1,766,767.9
BEGIN DESCRIPTION:
Cross Section K142-00-00-X8
END DESCRIPTION:
XS GIS Cut Line= 4
      3038782.33      13929458.9      3037569.35     13928790.46
      3037460.13     13928758.27      3036317.42      13928391.9
#Sta/Elev= 30
  3583.5  144.92  3723.5  141.98  4103.5  141.25  4213.5  142.82  4233.5  140.94
  4253.5  136.41  4333.5  141.65  4750.3  136.56  4904.9  137.52  4939.2  138.38
  4973.6   126.2  4987.4  125.91  4994.2  122.96  4995.5     121  5003.3  121.51
  5011.6  124.96  5024.8  126.31  5053.9  136.68  5104.7  136.64  5166.6  136.93
  5242.8  141.47  5292.8   141.8  5392.8  139.22  5472.8   140.1  5502.8  142.46
  5642.8  143.08  5902.8  141.01  6002.8  141.64  6092.8  139.72  6282.8  143.11
#Mann= 7 ,-1 , 0
  3583.5     .99       0  4333.5      .1       0  4904.9    .045       0
  4939.2     .04       0  5053.9    .045       0  5104.7     .06       0
  5292.8     .99       0
#XS Ineff= 2 , 0
       0  4939.2  138.38  5053.9       0  136.68
Permanent Ineff=
       F       F
Bank Sta=4939.2,5053.9
XS Rating Curve= 0 ,0
Exp/Cntr=0.3,0.1

Type RM Length L Ch R = 1 ,15926   ,889.5,907,923.9
BEGIN DESCRIPTION:
Cross Section K142-00-00-X7
END DESCRIPTION:
XS GIS Cut Line= 4
      3038816.46      13928868.1      3037895.03     13928117.21
      3037722.03     13928039.01      3036562.63      13927473.3
#Sta/Elev= 30
    3729   142.2    3889   140.2    3909   141.8    4249     142    4449   139.5
    4489   134.6    4510   137.9  4903.6  137.01  4940.9  136.91    4994  121.71
    5007  121.99  5013.9  125.64  5055.5   136.8  5074.3  136.12  5091.7  135.25
  5278.5   141.7  5348.5  138.63  5398.5  141.88  5498.5  140.77  5548.5  142.46
  5608.5  141.91  5688.5  138.79  5748.5  142.76  5848.5  143.69  5928.5  142.89
  5998.5  139.76  6038.5  142.36  6118.5   143.1  6268.5  139.56  6398.5  141.78
#Mann= 7 ,-1 , 0
    3729     .99       0    4510      .1       0  4903.6    .045       0
  4940.9     .04       0  5055.5    .045       0  5074.3      .1       0
  5278.5     .99       0
#XS Ineff= 2 , 0
       0  4940.9  136.91  5055.5       0   136.8
Permanent Ineff=
       F       F
Bank Sta=4940.9,5055.5
XS Rating Curve= 0 ,0
Exp/Cntr=0.3,0.1

Type RM Length L Ch R = 1 ,15019   ,94.9,97,94.8
BEGIN DESCRIPTION:
K142-00-00-S05_PIPELINE - US - XS4
END DESCRIPTION:
XS GIS Cut Line= 4
      3039250.81      13928509.9      3038509.76      13927550.5
      3038440.18     13927386.68      3038001.81     13926141.57
#Sta/Elev= 30
  3707.7  141.45  3797.7  141.73  3877.7   139.8  4047.7  141.06  4457.7  140.42
  4557.7  136.73  4677.7  135.11  4737.7  135.23  4827.7  137.66  4897.7  137.36
  4917.7  137.78    4930  135.81    4950  129.48 4963.44  130.04 4998.37  120.06
 5020.74  121.39 5039.36  128.34    5050   137.2    5060  138.07    5080  137.44
    5098  138.18    5138   138.6    5188  137.76    5228  135.53    5268  137.11
    5558  137.98    5568  137.26    5608  138.79    5878  139.54    6418  139.88
#Mann= 7 ,-1 , 0
  3707.7     .99       0  4677.7      .1       0  4827.7    .045       0
  4897.7     .04       0    5098    .045       0    5138      .1       0
    5268     .99       0
#XS Ineff= 2 , 0
       0  4823.5  135.77  5180.8       0  135.89
Permanent Ineff=
       F       F
Bank Sta=4917.7,5050
XS Rating Curve= 0 ,0
Exp/Cntr=0.5,0.3

Type RM Length L Ch R = 1 ,14922   ,20,20,20.1
BEGIN DESCRIPTION:
K142-00-00-S05_PIPELINE - US - XS3
END DESCRIPTION:
XS GIS Cut Line= 4
      3039346.29      13928492.5      3038605.24     13927533.13
      3038535.67     13927369.32      3038097.29      13926124.2
#Sta/Elev= 30
  3704.4  141.92  3904.4  139.93  3964.4  141.21  4204.4  139.91  4234.4  140.68
  4364.4  137.85  4414.4  140.26  4694.4  137.08  4714.4  135.79  4744.4  135.84
  4774.4  137.62  4844.4  137.98 4856.36  136.46 4923.16  137.01 4933.46  137.29
 4940.26  136.91 4998.86  119.88 5021.56  120.95 5040.46  128.24 5070.96  137.96
 5079.86  137.86  5125.3  136.75  5165.3  138.04  5205.3  138.48  5345.3  135.91
  5370.5  136.18  5375.5  137.09  5585.5  137.76  5735.5  139.81  6415.5  139.77
#Mann= 7 ,-1 , 0
  3704.4     .99       0  4774.4      .1       0 4923.16    .045       0
 4933.46     .04       0 5070.96    .045       0 5079.86      .1       0
  5165.3     .99       0
#XS Ineff= 2 , 0
       0  4923.5  135.77  5080.8       0  135.89
Permanent Ineff=
       F       F
Bank Sta=4933.46,5070.96
XS Rating Curve= 0 ,0
Exp/Cntr=0.5,0.3

Type RM Length L Ch R = 3 ,14912   ,,,
BEGIN DESCRIPTION:
PL1_K142-00-00-S05;Near Kathy Rd
END DESCRIPTION:
Bridge Culvert--1,0,-1,-1, 0
Deck Dist Width WeirC Skew NumUp NumDn MinLoCord MaxHiCord MaxSubmerge Is_Ogee
10,1,2.6,0, 29, 29, , , 0.95, 0, ,,,
 4923.16  4933.1 4933.16 4933.27 4933.36 4933.46 4935.36 4936.26 4940.26 4963.26
 4976.56 4984.36 4994.06 4996.06 4998.86 5004.16 5005.86 5011.66 5021.56 5025.86
 5040.46 5066.56 5069.76 5070.46 5070.96 5071.55 5071.66 5071.76 5079.86
  136.99  137.26  137.36  137.43  137.49  137.55  138.74  138.74  138.74  138.73
  138.72  138.72  138.72  138.72  138.72  138.71  138.71  138.71  138.71  138.71
   138.7  138.69  138.69  138.69  138.44  138.15  138.09  137.93  137.84
  136.99  137.26  137.26  137.26  137.27  137.27  137.91  137.91  137.91   137.9
  137.89  137.89  137.89  137.89  137.89  137.88  137.88  137.88  137.88  137.88
  137.87  137.86  137.86  137.86  137.94  137.93  137.93  137.93  137.84
 4923.16  4933.1 4933.16 4933.27 4933.36 4933.46 4935.36 4936.26 4940.26 4963.26
 4976.56 4984.36 4994.06 4996.06 4998.86 5004.16 5005.86 5011.66 5021.56 5025.86
 5040.46 5066.56 5069.76 5070.46 5070.96 5071.55 5071.66 5071.76 5079.86
  136.99  137.26  137.36  137.43  137.49  137.55  138.74  138.74  138.74  138.73
  138.72  138.72  138.72  138.72  138.72  138.71  138.71  138.71  138.71  138.71
   138.7  138.69  138.69  138.69  138.44  138.15  138.09  137.93  137.84
  136.99  137.26  137.26  137.26  137.27  137.27  137.91  137.91  137.91   137.9
  137.89  137.89  137.89  137.89  137.89  137.88  137.88  137.88  137.88  137.88
  137.87  137.86  137.86  137.86  137.94  137.93  137.93  137.93  137.84
Pier Skew, UpSta & Num, DnSta & Num=  ,4936.3, 2 ,4936.3, 2 , 0 , 0 , 0 ,,
     1.2     1.2
  135.93  138.91
     1.2     1.2
  135.93  138.91
Pier Skew, UpSta & Num, DnSta & Num=  ,4976.6, 2 ,4976.6, 2 , 0 , 0 , 0 ,,
     1.2     1.2
  124.68  138.89
     1.2     1.2
  124.68  138.89
Pier Skew, UpSta & Num, DnSta & Num=  ,5025.9, 2 ,5025.9, 2 , 0 , 0 , 0 ,,
     1.2     1.2
  121.54  138.88
     1.2     1.2
  121.54  138.88
Pier Skew, UpSta & Num, DnSta & Num=  ,5066.6, 2 ,5066.6, 2 , 0 , 0 , 0 ,,
     1.2     1.2
  135.67  138.86
     1.2     1.2
  135.67  138.86
BR Coef= 1 , 1 , 1 ,1.25, 0 ,,,0.8,0,2,0,
WSPro=,,,, 1 ,,,, 0 ,,,, 0 ,,,,-1 ,-1 ,-1 , 0 , 0 , 0 , 0 , 0
BC Design=,, 0 ,, 0 ,,,,,,
BC HTab HWMax=141.92
BC Use User HTab Curves=0
BC User HTab FreeFlow(D)= 0

Type RM Length L Ch R = 1 ,14902   ,100,100,100.2
BEGIN DESCRIPTION:
K142-00-00-S05_PIPELINE - DS - XS2
END DESCRIPTION:
XS GIS Cut Line= 4
      3039372.14      13928472.3      3038621.99     13927521.41
      3038550.77     13927353.71      3038130.36      13926106.3
#Sta/Elev= 30
  3704.4  141.92  3904.4  139.93  3964.4  141.21  4204.4  139.91  4234.4  140.68
  4364.4  137.85  4414.4  140.26  4694.4  137.08  4714.4  135.79  4744.4  135.84
  4774.4  137.62  4844.4  137.98 4856.36  136.46 4923.16  137.01 4933.46  137.29
 4940.26  136.91 4998.86  119.88 5021.56  120.95 5040.46  128.24 5070.96  137.96
 5079.86  137.86  5125.3  136.75  5165.3  138.04  5205.3  138.48  5345.3  135.91
  5370.5  136.18  5375.5  137.09  5585.5  137.76  5735.5  139.81  6415.5  139.77
#Mann= 7 ,-1 , 0
  3704.4     .99       0  4774.4      .1       0 4923.16    .045       0
 4933.46     .04       0 5070.96    .045       0 5079.86      .1       0
  5165.3     .99       0
#XS Ineff= 2 , 0
       0  4923.5  135.77  5080.8       0  135.89
Permanent Ineff=
       F       F
Bank Sta=4933.46,5070.96
XS Rating Curve= 0 ,0
Exp/Cntr=0.5,0.3

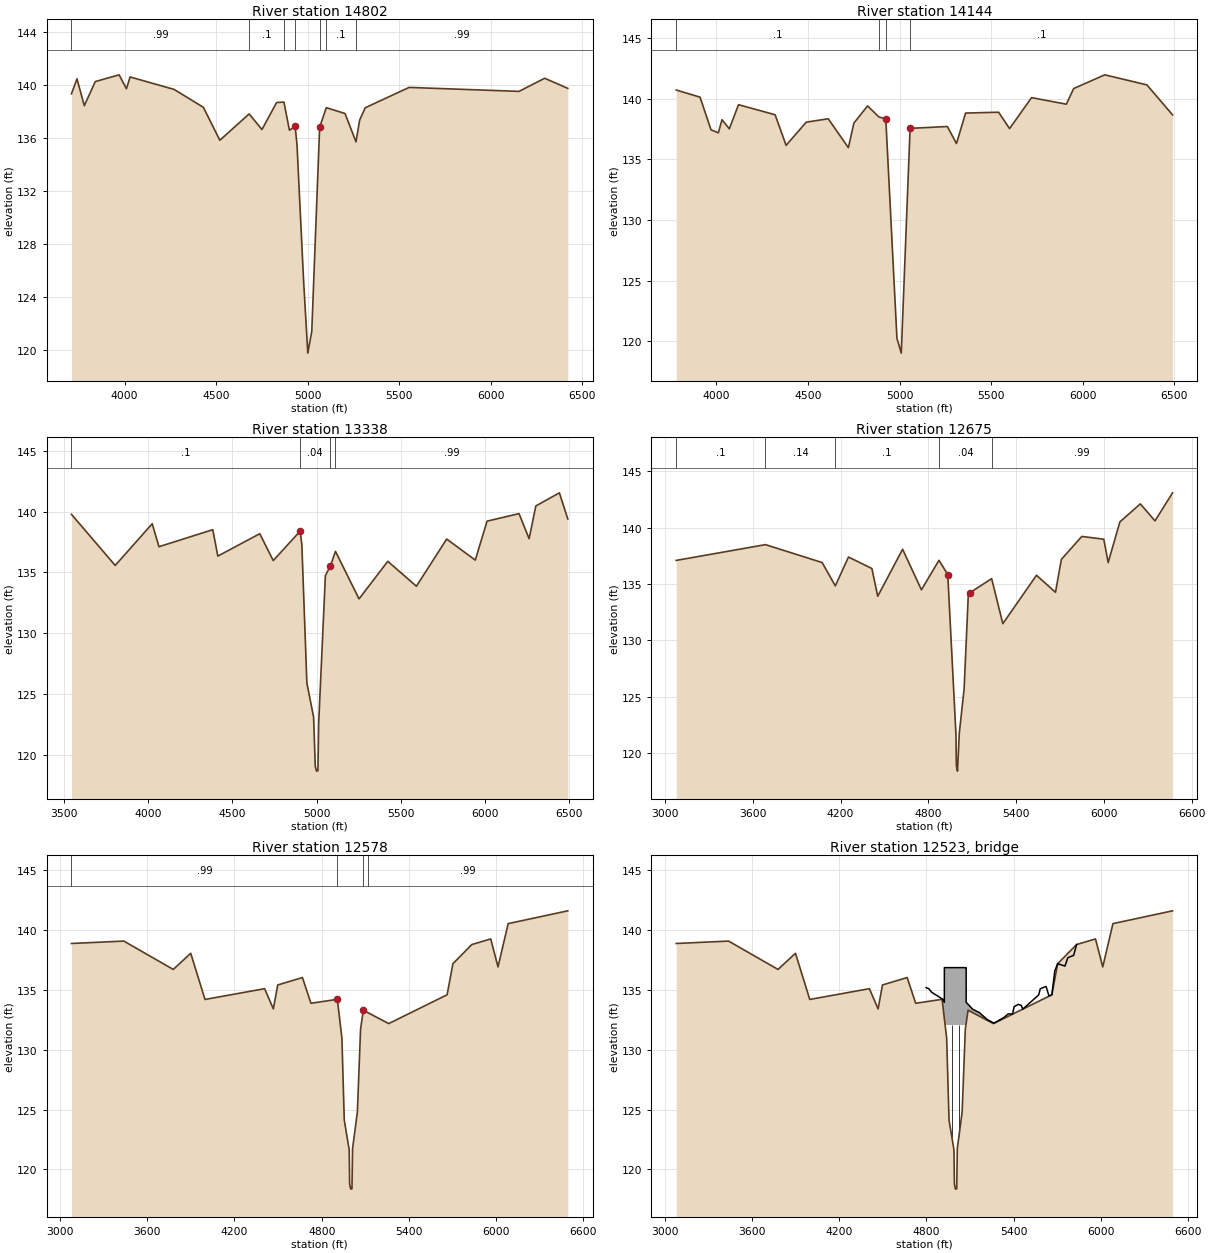
Type RM Length L Ch R = 1 ,14802   ,648.5,658,663.4
BEGIN DESCRIPTION:
K142-00-00-S05_PIPELINE - DS - XS1
END DESCRIPTION:
XS GIS Cut Line= 4
      3039463.29      13928431.1      3038713.14     13927480.17
      3038641.91     13927312.48      3038221.51     13926065.07
#Sta/Elev= 30
  3710.1  139.35  3740.1  140.48  3780.1  138.45  3840.1  140.27  3970.1  140.78
  4010.1  139.73  4030.1  140.62  4270.1  139.68  4430.1  138.33  4520.1  135.84
  4680.1  137.83  4750.1  136.65  4830.1  138.69  4870.1  138.72  4900.1   136.6
  4931.3  136.88  4941.3  135.53 4977.12  125.31 5000.28  119.77 5021.99  121.41
 5065.04  136.82  5101.3   138.3  5203.5  137.86  5263.5  135.72  5283.5  137.36
  5313.5  138.29  5553.5  139.83  6153.5  139.53  6293.5  140.52  6419.9  139.76
#Mann= 7 ,-1 , 0
  3710.1     .99       0  4680.1      .1       0  4870.1    .045       0
  4931.3     .04       0 5065.04    .045       0  5101.3      .1       0
  5263.5     .99       0
#XS Ineff= 2 , 0
       0  4823.5  135.77  5180.8       0  135.89
Permanent Ineff=
       F       F
Bank Sta=4931.3,5065.04
XS Rating Curve= 0 ,0
Exp/Cntr=0.3,0.1

Type RM Length L Ch R = 1 ,14144   ,800.9,806,799.4
BEGIN DESCRIPTION:
Cross Section K142-00-00-X6
END DESCRIPTION:
XS GIS Cut Line= 4
 3039893.124570513928229.2692621      3039308.88     13927289.71
      3039293.87     13927137.17 3038980.420614913925721.4933787
#Sta/Elev= 30
  3780.8  140.71  3910.8  140.12  3970.8  137.43  4010.8  137.18  4030.8  138.26
  4070.8  137.51  4120.8   139.5  4320.8  138.67  4380.8  136.15  4490.8  138.06
  4610.8  138.34  4720.8  135.96  4750.8  137.98  4825.6   139.4  4888.4  138.48
  4925.1  138.34    4986  120.26  5009.7  119.03  5057.9  137.55  5261.2   137.7
  5311.2   136.3  5361.1  138.81  5541.1  138.88  5601.1  137.53  5721.1  140.08
  5911.1  139.54  5951.1  140.83  6121.1  141.96  6351.1  141.13  6491.1  138.66
#Mann= 4 ,-1 , 0
  3780.8      .1       0  4888.4    .045       0  4925.1     .04       0
  5057.9      .1       0
Bank Sta=4925.1,5057.9
XS Rating Curve= 0 ,0
Exp/Cntr=0.3,0.1

Type RM Length L Ch R = 1 ,13338   ,675.4,663,640.7
BEGIN DESCRIPTION:
Interpolated XS
END DESCRIPTION:
XS GIS Cut Line= 4
      3040537.78      13928465.4      3040147.22      13927528.8
      3040043.81      13926694.1      3039489.59      13925745.9
#Sta/Elev= 30
  3542.9  139.78  3802.9  135.58  4022.9  139.01  4062.9  137.12  4382.9  138.52
  4412.9  136.35  4662.3  138.19  4742.3  135.98  4902.3   138.4  4912.3  137.32
  4942.3  125.91  4982.3  123.11  4992.1  119.07  4999.6  118.67    5008   118.7
  5012.3  122.55  5052.3  134.74  5082.3  135.54  5112.3  136.74  5252.3  132.83
  5423.4  135.92  5593.4  133.87  5773.4  137.75  5943.4  136.02  6013.4  139.22
  6203.4  139.84  6263.4  137.78  6303.4  140.47  6443.4  141.55  6493.4   139.4
#Mann= 4 ,-1 , 0
  3542.9      .1       0  4902.3     .04       0  5082.3    .045       0
  5112.3     .99       0
Bank Sta=4902.3,5082.3
XS Rating Curve= 0 ,0
Exp/Cntr=0.3,0.1

Type RM Length L Ch R = 1 ,12675   ,97.8,97,96.7
BEGIN DESCRIPTION:
K142-00-00-S4_ELDRIDGE - US - XS4
END DESCRIPTION:
XS GIS Cut Line= 5
      3041586.54      13928589.7      3041438.95     13927704.77
      3040918.21     13927167.06        3040532.     13926739.19
      3039788.74     13925809.81
#Sta/Elev= 30
  3077.3   137.1  3687.3   138.5  4074.5  136.91  4164.5  134.84  4254.5   137.4
  4414.5  136.38  4454.5  133.92  4624.5  138.09  4753.1  134.49  4873.1  137.11
  4933.1  135.84 4988.92   121.7 4992.04  118.84  4999.6  118.39 5012.03  121.76
 5045.03  125.71  5073.1  133.94  5083.1  134.22  5233.1  135.48  5309.5  131.48
  5539.5  135.78  5669.5  134.27  5709.5  137.19  5849.5  139.23  5999.5  138.98
  6029.5  136.91  6109.5  140.52  6249.5  142.12  6349.5  140.61  6469.5   143.1
#Mann= 5 ,-1 , 0
  3077.3      .1       0  3687.3     .14       0  4164.5      .1       0
  4873.1     .04       0  5233.1     .99       0
#XS Ineff= 2 , 0
       0  4797.5   133.8  5196.2       0  132.25
Permanent Ineff=
       F       F
Bank Sta=4933.1,5083.1
XS Rating Curve= 0 ,0
Exp/Cntr=0.5,0.3

Type RM Length L Ch R = 1 ,12578   ,110.5,110,109.5
BEGIN DESCRIPTION:
K142-00-00-S4_ELDRIDGE - US - XS3
END DESCRIPTION:
XS GIS Cut Line= 5
      3041660.32      13928526.8      3041512.73     13927641.84
      3040991.99     13927104.12      3040605.79     13926676.25
      3039862.52      13925746.8
#Sta/Elev= 30
  3079.1  138.89  3439.1  139.09  3779.1  136.72  3899.1  138.07  3997.4  134.21
  4407.4  135.11  4467.4  133.42  4497.4  135.42  4667.4  136.04  4725.9  133.89
  4907.5  134.22  4938.9  130.96  4955.1  124.12    4989  121.64  4992.1  118.75
  4999.6  118.35    5008  118.38  5012.1  121.74  5045.3   124.8  5067.1  131.72
  5086.2  133.31  5116.9  133.11  5260.8  132.19  5662.3   134.6  5702.3   137.2
  5832.3   138.8  5962.3  139.27  6012.3  136.93  6082.3  140.55  6492.3  141.62
#Mann= 4 ,-1 , 0
  3079.1     .99       0  4907.5     .04       0  5086.2    .045       0
  5116.9     .99       0
#XS Ineff= 2 , 0
       0  4897.5   133.8  5096.2       0  132.25
Permanent Ineff=
       F       F
Bank Sta=4907.5,5086.2
XS Rating Curve= 0 ,0
Exp/Cntr=0.5,0.3

Type RM Length L Ch R = 3 ,12523   ,,,
BEGIN DESCRIPTION:
ELDRIDGE
Structure ID: K142-00-00-S4
END DESCRIPTION:
Bridge Culvert--1,0,-1,-1, 0
Deck Dist Width WeirC Skew NumUp NumDn MinLoCord MaxHiCord MaxSubmerge Is_Ogee
10,88,2.6,0, 55, 55, , , 0.95, 0, ,,,
  4797.3  4815.9  4835.9  4907.5  4911.2  4911.4 4922.97 4923.08 4923.19 4923.31
  4923.4 4928.09  4938.9  4955.1  4963.3    4989  4992.1  4999.6    5008  5012.1
  5018.3  5025.1  5045.3  5067.1 5071.32 5072.89    5073 5073.11 5073.19  5073.3
  5086.2  5116.9  5163.8    5218  5260.8  5267.6  5332.3  5362.3  5392.3  5402.3
  5432.3  5452.3  5462.3    5526  5572.3  5582.3  5622.3  5642.3  5662.3  5682.3
  5702.3  5752.3  5772.3  5812.3  5832.3
   135.2  135.11  134.81  134.26  134.25  134.25  133.97  136.87  136.87  136.87
  136.87  136.87  136.87  136.87  136.87  136.87  136.87  136.87  136.87  136.87
  136.87  136.87  136.87  136.87  136.87  136.87  136.87  133.97  133.97  133.97
   133.8   133.4  133.11  132.53  132.25  132.25   132.7     133     133   133.6
   133.8   133.7   133.4  134.09   134.6   135.1   135.3   134.5   134.6   136.6
   137.2     137   137.7   137.9   138.8
  135.19   135.1   134.8  134.22  133.83  133.81   132.6  132.59  132.58  132.57
  132.56  132.07  132.07  132.07  132.07  132.07  132.07  132.07  132.07  132.07
  132.07  132.07  132.07  132.07  132.07   132.2  132.21  132.22  132.23  132.24
  133.31  133.11  132.81  132.46  132.19  132.24   132.7     133     133   133.6
   133.8   133.7   133.4  134.09   134.6   135.1   135.3   134.5   134.6   136.6
   137.2     137   137.7   137.9   138.8
  4797.3  4815.9  4835.9  4907.5  4911.2  4911.4 4922.97 4923.08 4923.19 4923.31
  4923.4 4928.09  4938.9  4955.1  4963.3    4989  4992.1  4999.6    5008  5012.1
  5018.3  5025.1  5045.3  5067.1 5071.32 5072.89    5073 5073.11 5073.19  5073.3
  5086.2  5116.9  5163.8    5218  5260.8  5267.6  5332.3  5362.3  5392.3  5402.3
  5432.3  5452.3  5462.3    5526  5572.3  5582.3  5622.3  5642.3  5662.3  5682.3
  5702.3  5752.3  5772.3  5812.3  5832.3
     134   134.7  134.81  134.26  134.25  134.25  133.97  136.87  136.87  136.87
  136.87  136.87  136.87  136.87  136.87  136.87  136.87  136.87  136.87  136.87
  136.87  136.87  136.87  136.87  136.87  136.87  136.87  133.97  133.97  133.97
   133.8   133.4  133.11  132.53  132.25  132.25   132.7     133     133   133.6
   133.8   133.7   133.4  134.09   134.6   135.1   135.3   134.5   134.6   136.6
   137.2     137   137.7   137.9   138.8
     134     134     134     133     133     133     132     132     132     132
     132  131.65  131.65  131.65  131.65  131.65  131.65  131.65  131.65  131.65
  131.65  131.65  131.65  131.65  131.65     131     131     131     131     131
     131     131     131     131     131     131     131     131     131     131
     131     131     131     131     131     131     131     131     131     131
     131     131     131     131     131
Pier Skew, UpSta & Num, DnSta & Num=  ,4973.9, 2 ,4973.9, 2 , 0 , 0 , 0 ,,
     1.3     1.3
   121.7  133.07
     1.3     1.3
  121.28  132.65
Pier Skew, UpSta & Num, DnSta & Num=  ,5023.9, 2 ,5023.9, 2 , 0 , 0 , 0 ,,
     1.3     1.3
  121.24  133.07
     1.3     1.3
  120.82  132.65
BR Coef= 1 , 1 , 1 ,1.25, 0 ,,,0.8,0,2,0,
WSPro=,,,, 1 ,,,, 0 ,,,, 0 ,,,,-1 ,-1 ,-1 , 0 , 0 , 0 , 0 , 0
BC Design=,, 0 ,, 0 ,,,,,,
BC HTab HWMax=141.73
BC Use User HTab Curves=0
BC User HTab FreeFlow(D)= 0

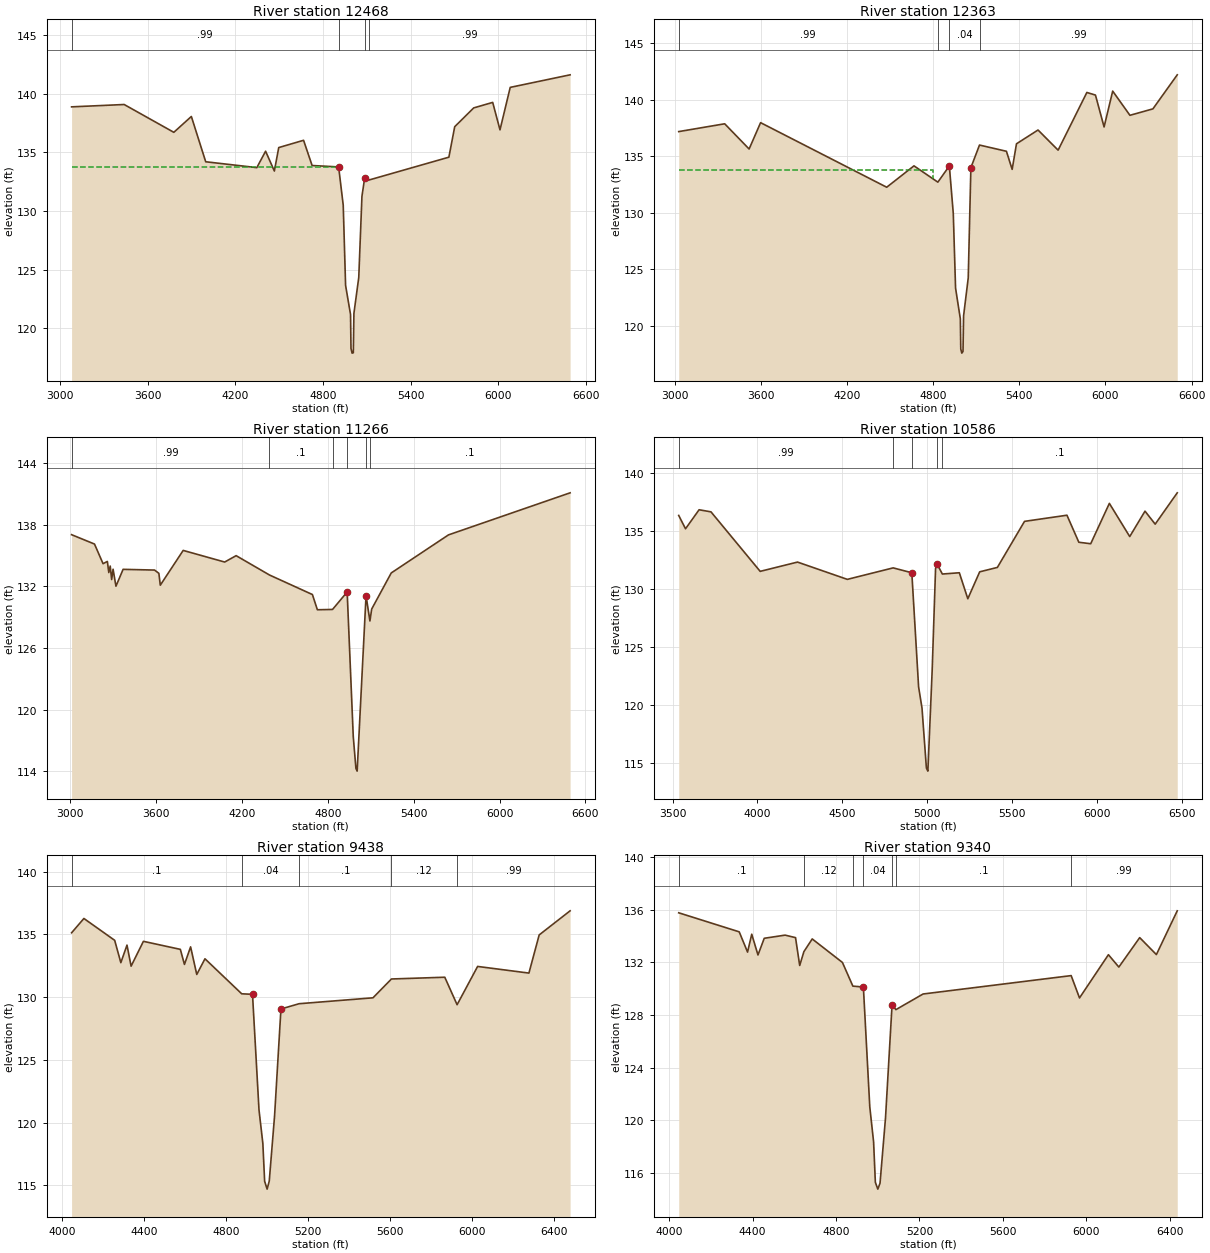
Type RM Length L Ch R = 1 ,12468   ,104,105,105.3
BEGIN DESCRIPTION:
K142-00-00-S4_ELDRIDGE - DS - XS2
END DESCRIPTION:
XS GIS Cut Line= 5
      3041789.03      13928508.7      3041645.08     13927622.41
      3041083.83     13927043.68      3040696.93     13926615.03
      3039954.03      13925686.1
#Sta/Elev= 30
  3079.1  138.89  3439.1  139.09  3779.1  136.72  3899.1  138.07  3997.4  134.21
  4347.4  133.71  4407.4  135.11  4467.4  133.42  4497.4  135.42  4667.4  136.04
  4725.9  133.89  4907.5  133.77  4938.9  130.51  4955.1  123.67    4989  121.19
  4992.1   118.3  4999.6   117.9    5008  117.93  5012.1  121.29  5045.3  124.35
  5067.1  131.27  5086.2  132.86  5116.9  132.66  5662.3   134.6  5702.3   137.2
  5832.3   138.8  5962.3  139.27  6012.3  136.93  6082.3  140.55  6492.3  141.62
#Mann= 4 ,-1 , 0
  3079.1     .99       0  4907.5     .04       0  5086.2    .045       0
  5116.9     .99       0
#XS Ineff= 2 , 0
       0 4900.83   133.8 5092.87       0  132.25
Permanent Ineff=
       F       F
Bank Sta=4907.5,5086.2
XS Rating Curve= 0 ,0
Exp/Cntr=0.5,0.3

Type RM Length L Ch R = 1 ,12363   ,1075.3,1097,1088.2
BEGIN DESCRIPTION:
K142-00-00-S4_ELDRIDGE - DS - XS1
END DESCRIPTION:
XS GIS Cut Line= 5
      3041878.01      13928456.7      3041734.06     13927570.32
      3041172.81     13926991.59      3040785.91     13926562.95
      3040043.01     13925634.05
#Sta/Elev= 30
  3028.9  137.17  3348.9  137.86  3518.9  135.63  3598.9  137.96  4476.9  132.25
  4666.9  134.14  4833.1   132.7  4913.1  134.13 4940.53  129.93  4956.4  123.33
 4989.61  120.61 4992.65  117.95    5000  117.58  5008.2  117.73 5012.21  120.87
 5044.62  124.23  5063.1  133.98  5123.1  135.98  5310.5  135.43  5350.5  133.83
  5380.5  136.09  5530.5  137.31  5670.5  135.53  5870.5  140.63  5930.5   140.4
  5990.5  137.58  6050.5  140.75  6170.5  138.61  6330.5  139.18  6499.9  142.19
#Mann= 4 ,-1 , 0
  3028.9     .99       0  4833.1     .05       0  4913.1     .04       0
  5123.1     .99       0
#XS Ineff= 2 , 0
       0 4800.83   133.8 5192.87       0  132.25
Permanent Ineff=
       F       F
Bank Sta=4913.1,5063.1
XS Rating Curve= 0 ,0
Exp/Cntr=0.3,0.1

Type RM Length L Ch R = 1 ,11266   ,680,680,674.8
BEGIN DESCRIPTION:
Cross Section K142-00-00-X5
END DESCRIPTION:
XS GIS Cut Line= 4
      3043370.76      13927996.7      3042053.69     13926616.64
      3041987.93     13926475.39      3040959.81      13925495.9
#Sta/Elev= 30
  3008.6  137.02  3168.6  136.11  3228.6   134.2  3258.6  134.42  3268.6  133.34
  3278.6  133.97  3288.6  132.66  3298.6  133.66  3318.6  132.01  3368.6  133.65
  3588.6  133.58  3618.6  133.26  3628.6  132.11  3788.6  135.49  4078.6  134.36
  4158.6  134.98  4391.7   133.1  4691.7   131.2  4726.4  129.72  4832.3  129.75
  4934.6  131.45  4977.2  117.39  4995.7   114.3  5004.4  114.03  5066.5  131.09
  5093.6  128.63    5106  129.79  5242.7   133.3  5642.7     137  6492.7  141.09
#Mann= 6 ,-1 , 0
  3008.6     .99       0  4391.7      .1       0  4832.3    .045       0
  4934.6     .04       0  5066.5    .045       0  5093.6      .1       0
#XS Ineff= 2 , 0
       0  4934.6  131.45               0
Permanent Ineff=
       F       F
Bank Sta=4934.6,5066.5
XS Rating Curve= 0 ,0
Exp/Cntr=0.3,0.1

Type RM Length L Ch R = 1 ,10586   ,1142.8,1148,1134.5
BEGIN DESCRIPTION:
Interpolated XS
END DESCRIPTION:
XS GIS Cut Line= 4
      3043560.18      13927342.3      3042850.68     13926620.28
       3042400.1     13925859.47      3041471.56      13925348.1
#Sta/Elev= 30
  3536.2  136.32  3576.2  135.17  3656.2  136.81  3726.2  136.63  4016.2   131.5
  4236.2   132.3  4529.8  130.81  4799.8   131.8  4909.8  131.38  4949.8  121.54
  4969.8  119.72  4995.7  114.55  5004.4  114.28  5029.8  122.98  5049.8  131.75
  5059.8   132.1  5089.8  131.27  5189.8  131.38  5239.8  129.14  5309.8  131.46
    5414  131.84    5574  135.81    5824  136.34    5894  134.01    5964  133.88
    6074  137.36    6194   134.5    6284  136.69    6344  135.57    6474  138.27
#Mann= 5 ,-1 , 0
  3536.2     .99       0  4799.8    .045       0  4909.8     .04       0
  5059.8    .045       0  5089.8      .1       0
#Block Obstruct= 2 , 0
       0                    5060       0     132
Bank Sta=4909.8,5059.8
XS Rating Curve= 0 ,0
Exp/Cntr=0.3,0.1

Type RM Length L Ch R = 1 ,9438    ,101.9,98,93
BEGIN DESCRIPTION:
K142-00-00-S3A_WEIR - US - XS4
END DESCRIPTION:
XS GIS Cut Line= 5
      3044383.49      13926344.8      3043697.76     13925805.76
      3043580.88     13925673.57      3042211.29     13925704.52
      3042222.07     13925704.51
#Sta/Elev= 30
  4048.1  135.13  4108.1  136.27  4258.1  134.53  4288.1  132.75  4318.1  134.15
  4338.1  132.47  4398.1  134.45  4578.1  133.81  4598.1  132.61  4628.1  134.01
  4658.1  131.81  4698.1  133.06 4877.14  130.27 4929.76  130.23 4961.37  121.03
  4980.2  118.34 4988.85  115.34    5001  114.71 5011.43  115.36 5037.33  120.56
 5068.36  129.06  5156.8  129.48  5516.8  129.95  5606.8  131.45  5866.8  131.59
  5926.8   129.4  6026.8  132.45  6276.8  131.92  6326.8  134.96  6477.5  136.88
#Mann= 5 ,-1 , 0
  4048.1      .1       0 4877.14     .04       0  5156.8      .1       0
  5606.8     .12       0  5926.8     .99       0
#XS Ineff= 2 , 0
       0  4821.5  129.93  5179.1       0  128.03
Permanent Ineff=
       F       F
Bank Sta=4929.76,5068.36
XS Rating Curve= 0 ,0
Exp/Cntr=0.7,0.5

Type RM Length L Ch R = 1 ,9340    ,18.6,18,17.3
BEGIN DESCRIPTION:
K142-00-00-S3A_WEIR - US - XS3
END DESCRIPTION:
XS GIS Cut Line= 4
      3044452.93      13926275.4      3043759.53     13925715.19
       3043661.5     13925632.64      3042291.51       13925635.
#Sta/Elev= 30
  4046.2  135.78  4336.2  134.33  4376.2  132.79  4396.2  134.15  4426.2  132.57
  4456.2  133.84  4556.2  134.08  4606.2  133.89  4626.2  131.77  4646.2  132.82
  4686.2  133.79  4831.1     132  4881.1   130.2  4931.5  130.13  4962.2  121.01
  4980.5  118.34  4988.9  115.27  5000.7  114.75  5011.3   115.2  5037.6  120.17
  5069.1   128.8  5087.4  128.41  5217.7   129.6  5927.7     131  5967.7   129.3
  6106.3  132.59  6156.3  131.65  6256.3  133.89  6336.3   132.6  6436.3  135.93
#Mann= 7 ,-1 , 0
  4046.2      .1       0  4646.2     .12       0  4881.1    .045       0
  4931.5     .04       0  5069.1    .045       0  5087.4      .1       0
  5927.7     .99       0
#XS Ineff= 2 , 0
       0  4921.5  129.93  5079.1       0  128.03
Permanent Ineff=
       F       F
Bank Sta=4931.5,5069.1
XS Rating Curve= 0 ,0
Exp/Cntr=0.7,0.5