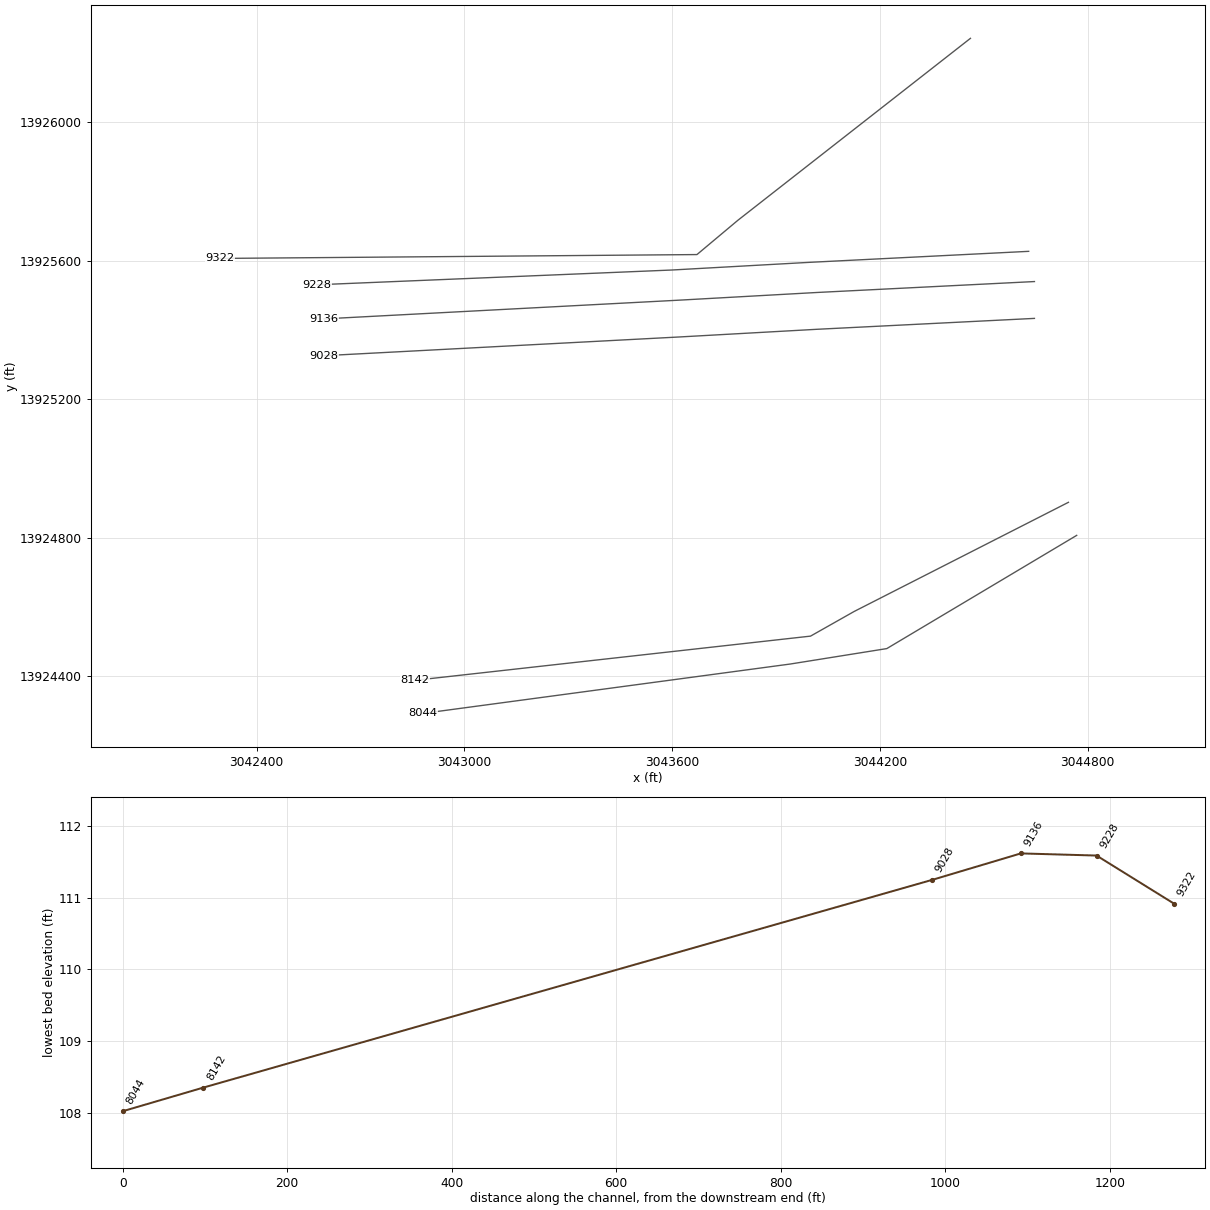
HEC-RAS study K142-00-00.prj: K142-00-00

--- K142-00-00.g01 (geometry) --- (continued)

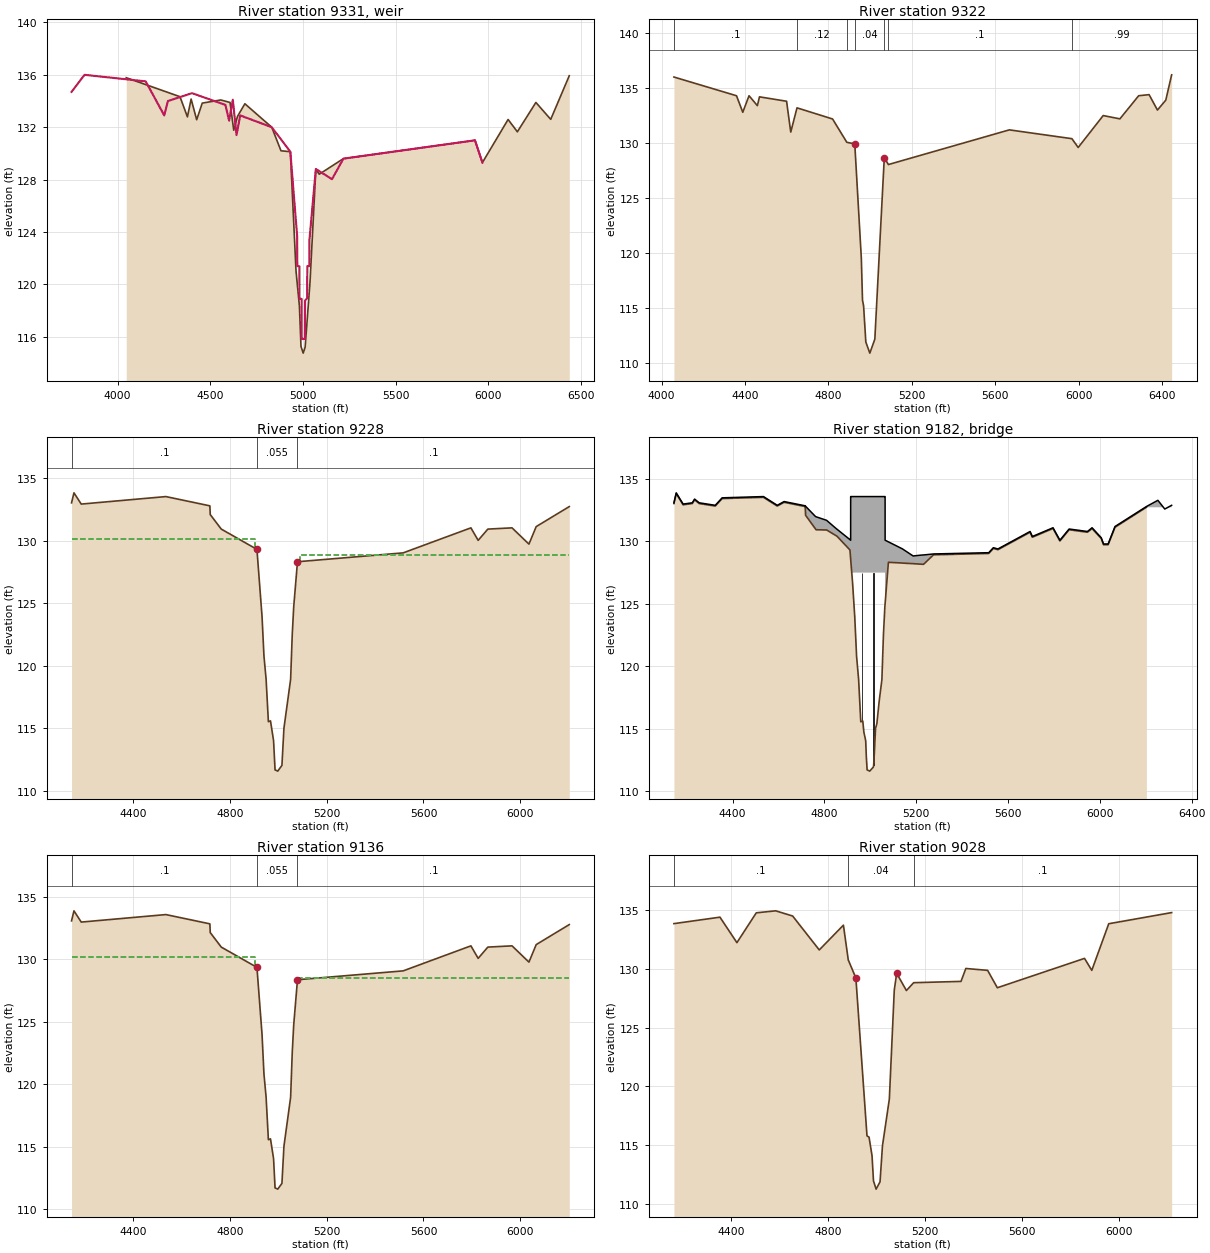
Type RM Length L Ch R = 5 ,9331    ,,,
BEGIN DESCRIPTION:
110' US OF LOUETTA
Structure ID: K142-00-00-S3A
END DESCRIPTION:
IW Pilot Flow=0
#Inline Weir SE= 30
  3751.1   134.7  3821.1     136  4151.1   135.5  4251.1   132.9  4271.1     134
  4401.1   134.6  4581.1   133.7  4601.1   132.5  4621.1   134.1  4641.1   131.4
  4661.1   132.9  4831.1     132  4931.5  130.13  4968.4  123.65    4969  121.39
  4980.6  121.38  4980.9  118.88  4992.5  118.89  4992.8  115.83  5010.3  115.83
  5010.9  118.77  5022.4  118.94    5023   121.4  5034.1  121.39  5034.5   123.4
  5069.1  128.81  5156.3  128.03  5217.7   129.6  5927.7     131  5967.7   129.3
IW Dist,WD,Coef,Skew,MaxSub,Min_El,Is_Ogee,SpillHt,DesHd
10,0.5,3,0,0.95,, 0 ,,,0.1,0.1,
Inline Weir Flap Gates= 0

Type RM Length L Ch R = 1 ,9322    ,118.4,94,70.9
BEGIN DESCRIPTION:
K142-00-00-S3A_WEIR - DS - XS2
Located At: 110' US OF LOUETTA
END DESCRIPTION:
XS GIS Cut Line= 4
      3044461.85      13926242.4      3043790.27     13925717.01
      3043671.79     13925617.77       3042293.7      13925606.6
#Sta/Elev= 30
  4059.1     136  4359.1   134.3  4389.1   132.8  4419.1   134.3  4459.1   133.4
  4469.1   134.2  4599.1   133.8  4619.1     131  4649.1   133.2  4819.6  132.19
  4887.9  130.07    4926  129.93  4957.4  119.57  4963.1  115.73  4968.3  115.22
    4979  111.93  4998.2  110.92  5022.2  112.19  5067.5  128.68  5087.2  128.05
    5667   131.2    5967   130.4    5997   129.6    6117   132.5    6197   132.2
    6287   134.3    6337   134.4    6377     133    6417   133.9  6445.1   136.2
#Mann= 7 ,-1 , 0
  4059.1      .1       0  4649.1     .12       0  4887.9    .045       0
    4926     .04       0  5067.5    .045       0  5087.2      .1       0
    5967     .99       0
Bank Sta=4926,5067.5
XS Rating Curve= 0 ,0
Exp/Cntr=0.7,0.5

Type RM Length L Ch R = 1 ,9228    ,88.6,92,93.5
BEGIN DESCRIPTION:
K142-00-00-S3_LOUETTA - US XS3
END DESCRIPTION:
XS GIS Cut Line= 4
      3044630.06      13925627.1      3043993.36     13925595.12
       3043598.9     13925573.12      3042574.41      13925530.5
#Sta/Elev= 30
  4144.9  133.04  4154.9  133.84  4184.9  132.94  4534.9  133.54  4716.8   132.8
  4718.4   132.1    4764  130.94  4911.5  129.32  4932.6  123.94  4940.5  120.79
  4949.4  118.93  4958.8  115.54  4967.5  115.61  4980.2  114.03  4986.4  111.69
  4997.6  111.59  5014.8  112.05  5023.1  115.02  5050.7  118.92  5057.5  122.53
  5063.5  124.72  5079.1  128.33  5516.2  129.04  5796.2  131.04  5826.2  130.04
  5866.2  130.94  5966.2  131.04  6036.2  129.74  6066.2  131.14  6202.9  132.74
#Mann= 3 ,-1 , 0
  4144.9      .1       0  4911.5    .055       0  5079.1      .1       0
#XS Ineff= 2 , 0
       0  4901.5  130.15  5089.1       0  128.84
Permanent Ineff=
       F       F
Bank Sta=4911.5,5079.1
XS Rating Curve= 0 ,0
Exp/Cntr=0.5,0.3

Type RM Length L Ch R = 3 ,9182    ,,,
BEGIN DESCRIPTION:
LOUETTA ROAD
Structure ID: K142-00-00-S3
END DESCRIPTION:
Bridge Culvert--1,0,-1,-1, 0
Deck Dist Width WeirC Skew NumUp NumDn MinLoCord MaxHiCord MaxSubmerge Is_Ogee
10,68,2.6,0, 82, 82, , , 0.95, 0, ,,,
  4144.9  4154.9  4184.9  4224.9  4234.9  4254.9  4324.9  4354.9  4534.9  4594.9
  4624.9  4716.5  4716.8  4718.4  4761.6    4764  4809.4  4810.2  4852.5  4854.7
  4911.5 4914.59  4914.7 4914.81 4914.91    4915 4919.72  4922.9    4923  4932.6
  4940.5  4949.4  4958.8  4967.5  4972.3  4980.2  4982.9  4986.4  4997.6  5013.3
  5014.8  5017.1  5019.2  5023.1  5028.8  5039.4  5050.7  5057.5  5063.4  5063.5
 5064.19  5064.3 5064.59  5064.7 5064.81  5079.1  5138.8  5139.1  5186.6  5229.5
  5232.4  5275.6  5322.7  5516.2  5536.2  5556.2  5636.2  5696.2  5706.2  5796.2
  5826.2  5866.2  5946.2  5966.2  6006.2  6016.2  6036.2  6066.2  6202.9  6252.9
  6282.9  6312.9
   133.1   133.9     133   133.1   133.4   133.1   132.9   133.5   133.6   132.9
   133.2  132.86  132.87  132.82     132  131.98   131.7  131.69  131.02  130.99
  130.15   130.1   133.6   133.6   133.6   133.6   133.6   133.6   133.6   133.6
   133.6   133.6   133.6   133.6   133.6   133.6   133.6   133.6   133.6   133.6
   133.6   133.6   133.6   133.6   133.6   133.6   133.6   133.6   133.6   133.6
   133.6   133.6   133.6   133.6   130.1  129.97  129.42  129.42  128.84  128.92
  128.92     129  129.02   129.1   129.5   129.4   130.2   130.8   130.4   131.1
   130.1     131   130.8   131.1   130.3   129.8   129.8   131.2   132.8   133.3
   132.6   132.9
                                                                                
                                                                                
                                                   127.5   127.5   127.5   127.5
   127.5   127.5   127.5   127.5   127.5   127.5   127.5   127.5   127.5   127.5
   127.5   127.5   127.5   127.5   127.5   127.5   127.5   127.5   127.5   127.5
   127.5  124.97  125.03  125.06  125.08
                                                                                
                                                                                
                
  4144.9  4154.9  4184.9  4224.9  4234.9  4254.9  4324.9  4354.9  4534.9  4594.9
  4624.9  4716.5  4716.8  4718.4  4761.6    4764  4809.4  4810.2  4852.5  4854.7
  4911.5 4914.59  4914.7 4914.81 4914.91    4915 4919.72  4922.9    4923  4932.6
  4940.5  4949.4  4958.8  4967.5  4972.3  4980.2  4982.9  4986.4  4997.6  5013.3
  5014.8  5017.1  5019.2  5023.1  5028.8  5039.4  5050.7  5057.5  5063.4  5063.5
 5064.19  5064.3 5064.59  5064.7 5064.81  5079.1  5138.8  5139.1  5186.6  5229.5
  5232.4  5275.6  5322.7  5516.2  5536.2  5556.2  5636.2  5696.2  5706.2  5796.2
  5826.2  5866.2  5946.2  5966.2  6006.2  6016.2  6036.2  6066.2  6202.9  6252.9
  6282.9  6312.9
   133.1   133.9     133   133.1   133.4   133.1   132.9   133.5   133.6   132.9
   133.2  132.86  132.87  132.82     132  131.98   131.7  131.69  131.02  130.99
  130.15   130.1   133.6   133.6   133.6   133.6   133.6   133.6   133.6   133.6
   133.6   133.6   133.6   133.6   133.6   133.6   133.6   133.6   133.6   133.6
   133.6   133.6   133.6   133.6   133.6   133.6   133.6   133.6   133.6   133.6
   133.6   133.6   133.6   133.6   130.1  129.97  129.42  129.42  128.84  128.92
  128.92     129  129.02   129.1   129.5   129.4   130.2   130.8   130.4   131.1
   130.1     131   130.8   131.1   130.3   129.8   129.8   131.2   132.8   133.3
   132.6   132.9
                                                                                
                                                                                
                                                   127.5   127.5   127.5   127.5
   127.5   127.5   127.5   127.5   127.5   127.5   127.5   127.5   127.5   127.5
   127.5   127.5   127.5   127.5   127.5   127.5   127.5   127.5   127.5   127.5
   127.5  124.97  125.03  125.06  125.08
                                                                                
                                                                                
                
Pier Skew, UpSta & Num, DnSta & Num=  ,4964.8, 2 ,4964.8, 2 , 0 , 0 , 0 ,,
     1.5     1.5
  114.64   128.5
     1.5     1.5
  114.64   128.5
Pier Skew, UpSta & Num, DnSta & Num=  ,5014.8, 2 ,5014.8, 2 , 0 , 0 , 0 ,,
     1.5     1.5
  111.04   128.5
     1.5     1.5
  111.04   128.5
BR Coef= 1 , 1 , 1 ,1.05, 0 ,,,0.8,-1,1.2,0,
WSPro=,,,, 1 ,,,, 0 ,,,, 0 ,,,,-1 ,-1 ,-1 , 0 , 0 , 0 , 0 , 0
BR U #Sta/Elev= 78
  4144.9  133.04  4154.9  133.84  4184.9  132.94  4224.9  133.04  4234.9  133.34
  4254.9  133.04  4324.9  132.84  4354.9  133.44  4534.9  133.54  4594.9  132.84
  4624.9  133.14  4716.5   132.8  4716.8   132.8  4718.4   132.1  4761.6     131
    4764  130.94  4809.4  130.92  4810.2  130.92  4852.5  130.45  4854.7  130.43
  4911.5  129.32 4914.59  128.61  4914.7  128.59 4914.81  128.56 4914.91  128.54
    4915  128.52  4922.9  126.72    4923   126.7  4932.6  123.94  4940.5  120.79
  4949.4  118.93  4958.8  115.54  4967.5  115.61  4972.3  114.71  4980.2  114.03
  4982.9  112.78  4986.4  111.69  4997.6  111.59  5013.3  111.91  5014.8  112.05
  5017.1  112.75  5019.2  113.54  5023.1  115.02  5028.8  115.39  5039.4  117.27
  5050.7  118.92  5057.5  122.53  5063.4  124.68  5063.5  124.72 5064.19  124.88
  5064.3  124.91 5064.59  124.97  5064.7     125 5064.81  125.02  5079.1  128.33
  5138.8  128.27  5139.1  128.27  5186.6  128.22  5229.5  128.17  5232.4  128.17
  5275.6  128.93  5322.7  128.95  5516.2  129.04  5536.2  129.44  5556.2  129.34
  5636.2  130.14  5696.2  130.74  5706.2  130.34  5796.2  131.04  5826.2  130.04
  5866.2  130.94  5946.2  130.74  5966.2  131.04  6006.2  130.24  6016.2  129.74
  6036.2  129.74  6066.2  131.14  6202.9  132.74
BR U #Mann= 3
  4144.9      .1  4911.5    .055  5079.1      .1
BR D #Sta/Elev= 78
  4144.9  133.07  4154.9  133.87  4184.9  132.97  4224.9  133.07  4234.9  133.37
  4254.9  133.07  4324.9  132.87  4354.9  133.47  4534.9  133.57  4594.9  132.87
  4624.9  133.17  4716.5  132.83  4716.8  132.83  4718.4  132.13  4761.6  131.03
    4764  130.97  4809.4  130.95  4810.2  130.95  4852.5  130.48  4854.7  130.46
  4911.5  129.35 4914.59  128.64  4914.7  128.62 4914.81  128.59 4914.91  128.57
    4915  128.55  4922.9  126.75    4923  126.73  4932.6  123.97  4940.5  120.82
  4949.4  118.96  4958.8  115.57  4967.5  115.64  4972.3  114.74  4980.2  114.06
  4982.9  112.81  4986.4  111.72  4997.6  111.62  5013.3  111.94  5014.8  112.08
  5017.1  112.78  5019.2  113.57  5023.1  115.05  5028.8  115.42  5039.4   117.3
  5050.7  118.95  5057.5  122.56  5063.4  124.71  5063.5  124.75 5064.19  124.91
  5064.3  124.94 5064.59     125  5064.7  125.03 5064.81  125.05  5079.1  128.36
  5138.8   128.3  5139.1   128.3  5186.6  128.25  5229.5   128.2  5232.4   128.2
  5275.6  128.96  5322.7  128.98  5516.2  129.07  5536.2  129.47  5556.2  129.37
  5636.2  130.17  5696.2  130.77  5706.2  130.37  5796.2  131.07  5826.2  130.07
  5866.2  130.97  5946.2  130.77  5966.2  131.07  6006.2  130.27  6016.2  129.77
  6036.2  129.77  6066.2  131.17  6202.9  132.77
BR D #Mann= 3
  4144.9      .1  4911.5    .055  5079.1      .1
BC Design=,, 0 ,, 0 ,,,,,,
BC HTab HWMax=133.84
BC Use User HTab Curves=0
BC User HTab FreeFlow(D)= 0

Type RM Length L Ch R = 1 ,9136    ,106.7,108,106.4
BEGIN DESCRIPTION:
K142-00-00-S3_LOUETTA - DS XS2
END DESCRIPTION:
XS GIS Cut Line= 5
 3044646.684186813925539.8134968      3044017.77     13925508.21
      3043622.99     13925486.19 3042635.648482213925434.1397787
 3042594.705336113925431.9813565
#Sta/Elev= 30
  4144.9  133.07  4154.9  133.87  4184.9  132.97  4534.9  133.57  4716.8  132.83
  4718.4  132.13    4764  130.97  4911.5  129.35  4932.6  123.97  4940.5  120.82
  4949.4  118.96  4958.8  115.57  4967.5  115.64  4980.2  114.06  4986.4  111.72
  4997.6  111.62  5014.8  112.08  5023.1  115.05  5050.7  118.95  5057.5  122.56
  5063.5  124.75  5079.1  128.36  5516.2  129.07  5796.2  131.07  5826.2  130.07
  5866.2  130.97  5966.2  131.07  6036.2  129.77  6066.2  131.17  6202.9  132.77
#Mann= 3 ,-1 , 0
  4144.9      .1       0  4911.5    .055       0  5079.1      .1       0
#XS Ineff= 2 , 0
       0 4904.83  130.15 5085.77       0   128.5
Permanent Ineff=
       F       F
Bank Sta=4911.5,5079.1
XS Rating Curve= 0 ,0
Exp/Cntr=0.5,0.3

Type RM Length L Ch R = 1 ,9028    ,870.3,886,907.7
BEGIN DESCRIPTION:
K142-00-00-S3_LOUETTA - DS XS1
END DESCRIPTION:
XS GIS Cut Line= 4
      3044646.68      13925433.4      3044017.77     13925401.87
      3043622.99     13925379.85      3042594.71     13925325.64
#Sta/Elev= 30
  4162.8  133.86  4352.8  134.41  4422.8  132.24  4502.8  134.78  4582.8  134.95
  4652.8  134.51  4762.8  131.62  4862.5  133.73  4882.5  130.77 4913.95  129.23
 4959.85  115.78  4968.3  115.68 4980.62   114.1 4986.64  111.95 4997.51  111.25
 5013.65  111.87 5023.72  114.94  5052.1  118.92  5072.5  128.21  5082.5  129.63
  5122.5  128.16  5152.5  128.83  5347.9  128.94  5367.9  130.04  5457.9  129.88
  5497.9   128.4  5857.9   130.9  5887.9  129.88  5957.9  133.85  6217.6   134.8
#Mann= 3 ,-1 , 0
  4162.8      .1       0  4882.5     .04       0  5152.5      .1       0
#XS Ineff= 2 , 0
       0 4804.83  130.15 5185.77       0   128.5
Permanent Ineff=
       F       F
Bank Sta=4913.95,5082.5
XS Rating Curve= 0 ,0
Exp/Cntr=0.3,0.1

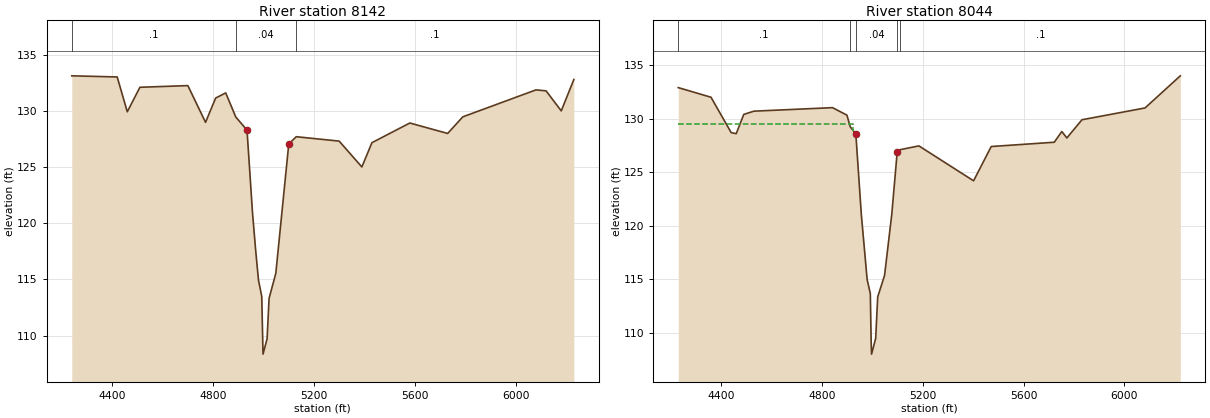
Type RM Length L Ch R = 1 ,8142    ,108.3,98,85.5
BEGIN DESCRIPTION:
K142-00-00-S02A_METAL BRIDGE - US - XS4
END DESCRIPTION:
XS GIS Cut Line= 4
      3044744.89      13924902.1      3044126.17     13924586.93
      3043999.92     13924515.57      3042857.11     13924387.91
#Sta/Elev= 30
    4239  133.12    4419  133.02    4459  129.92    4509   132.1    4699  132.25
    4769  128.98    4809  131.14    4849   131.6    4889  129.45  4933.4  128.29
 4954.99  120.97 4967.69  117.58 4978.78  114.94 4991.71  113.49 4996.78  108.35
 5012.89  109.71 5020.74  113.31 5047.45  115.54 5098.75  127.05  5128.4   127.7
  5298.4  127.31  5388.4  125.01  5428.4  127.17  5578.4  128.92  5728.4  127.99
  5788.4  129.47  6078.4  131.87  6118.4  131.78  6178.4     130  6228.3  132.79
#Mann= 3 ,-1 , 0
    4239      .1       0    4889     .04       0  5128.4      .1       0
#XS Ineff= 2 , 0
       0  4824.3  129.53  5208.4       0     127
Permanent Ineff=
       F       F
Bank Sta=4933.4,5098.75
XS Rating Curve= 0 ,0
Exp/Cntr=0.5,0.3

Type RM Length L Ch R = 1 ,8044    ,26.4,28,27.6
BEGIN DESCRIPTION:
K142-00-00-S02A_METAL BRIDGE - US - XS3
END DESCRIPTION:
XS GIS Cut Line= 4
      3044768.75      13924806.6      3044220.19     13924479.55
      3043941.41     13924434.96      3042880.97      13924292.4
#Sta/Elev= 30
  4229.9   132.9  4359.9     132  4439.9   128.7  4459.9   128.6  4489.9   130.4
  4529.9   130.7  4841.8  131.03    4899  130.33  4912.2  129.24  4934.3  128.59
  4956.3  121.01  4979.3  114.97  4991.8  113.67  4995.2  109.13  4996.7  108.02
  5013.1  109.49  5021.1  113.36  5048.3  115.37    5077  121.09  5098.4  126.88
  5111.1  127.11 5184.49  127.46  5401.4   124.2  5471.4   127.4  5721.4   127.8
  5751.4   128.8  5771.4   128.2  5831.4   129.9  6081.4     131  6221.4     134
#Mann= 5 ,-1 , 0
  4229.9      .1       0  4912.2    .045       0  4934.3     .04       0
  5098.4    .045       0  5111.1      .1       0
#XS Ineff= 2 , 0
       0  4924.3  129.53  5108.4       0     127
Permanent Ineff=
       F       F
Bank Sta=4934.3,5098.4
XS Rating Curve= 0 ,0
Exp/Cntr=0.5,0.3