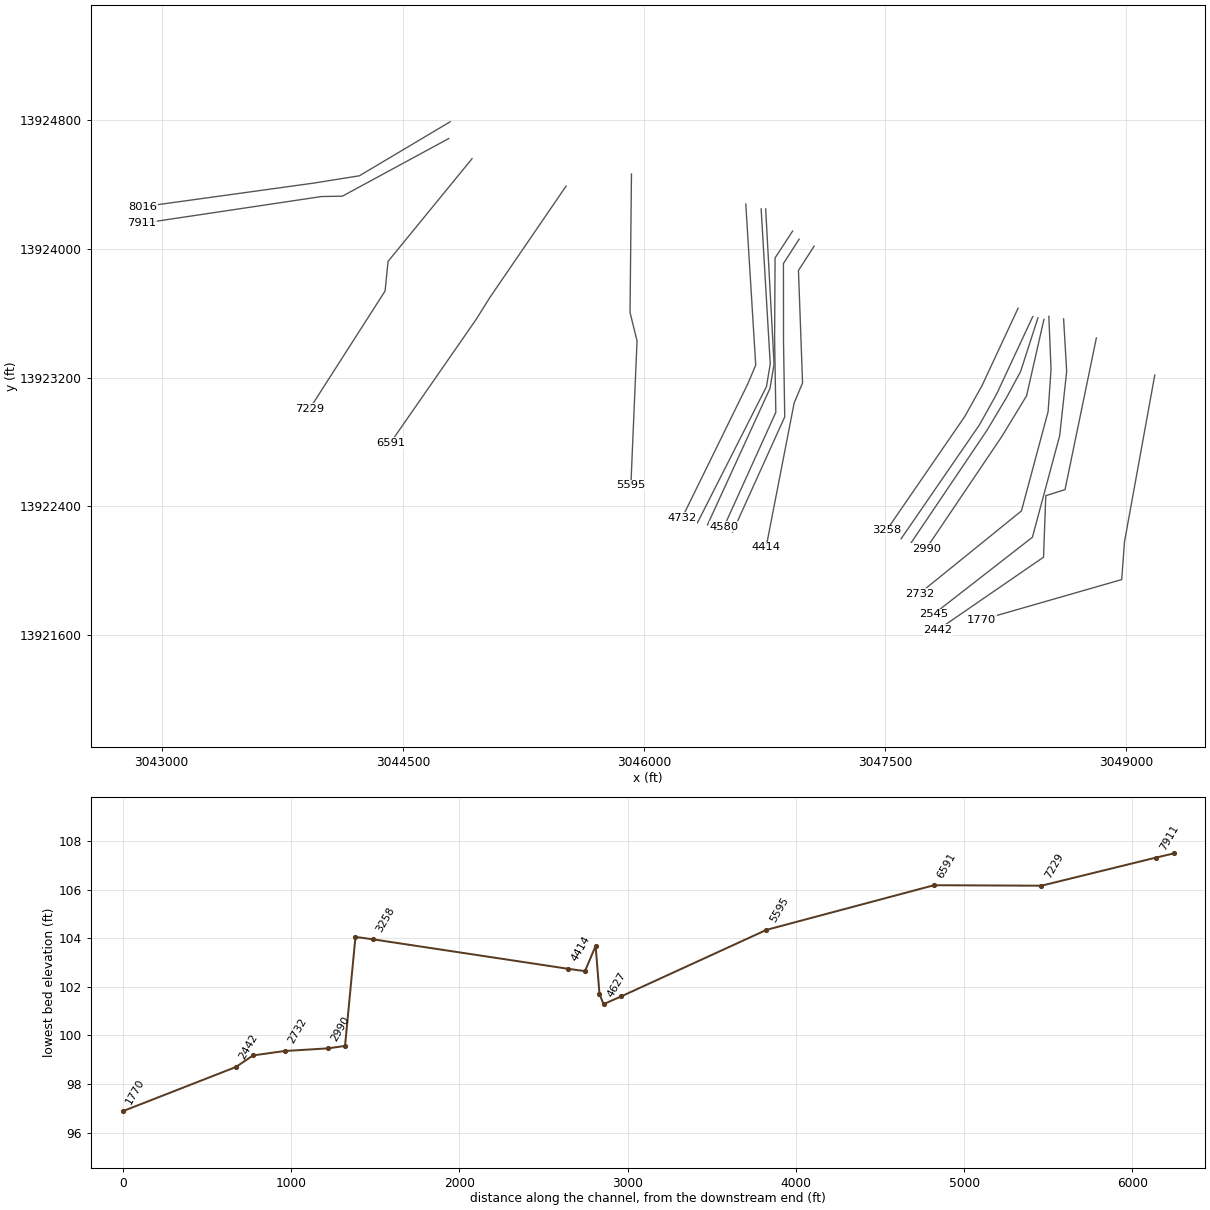
HEC-RAS study K142-00-00.prj: K142-00-00

--- K142-00-00.g01 (geometry) --- (continued)

Type RM Length L Ch R = 3 ,8030    ,,,
BEGIN DESCRIPTION:
METAL BRIDGE 1,100' DS LOUETTA; arched ped. bridge
Structure ID: K142-00-00-S02A
END DESCRIPTION:
Bridge Culvert--1,0,-1,-1, 0
Deck Dist Width WeirC Skew NumUp NumDn MinLoCord MaxHiCord MaxSubmerge Is_Ogee
10,7,2.6,0, 38, 40, , , 0.95, 0, ,,,
  4229.9  4299.9  4359.9  4419.9  4439.9  4459.9  4489.9  4529.9  4549.9  4599.9
  4701.8  4791.8  4841.8    4869    4899  4912.2  4934.3 4938.49  4938.6  4956.3
  5005.5  5051.1 5099.99  5100.1 5100.21 5184.49  5471.4  5711.4  5721.4  5741.4
  5751.4  5771.4  5831.4  5921.4  6081.4  6151.4  6211.4  6221.4
   132.9   132.2     132   130.1   128.7   128.6   130.4   130.7   130.4   130.6
  130.43  130.43  131.03  130.43  130.31  129.83  129.53  129.47  133.97  134.47
  135.88   135.7  133.97  133.97  129.47  128.84  126.97  127.67  127.36   127.8
  128.32  127.71  129.47  130.01  130.55  132.44  133.13  133.48
   132.9   132.2     132   130.1   128.7   128.6   130.4   130.7   130.4   130.6
  130.43  130.43  131.03  130.43   130.3  129.21  128.56  127.12  127.08  127.47
  128.88   128.7  126.97     120     120     120     120     120     120     120
     120     120     120     120     120     120     120     120
  4229.9  4299.9  4359.9  4419.9  4439.9  4459.9  4489.9  4529.9  4549.9  4599.9
  4701.8  4791.8  4841.8    4869    4899  4912.2  4934.3 4938.31 4938.49  4938.6
 4938.71  4956.3  5005.5  5051.1 5099.99  5100.1 5100.21 5184.49  5471.4  5711.4
  5721.4  5741.4  5751.4  5771.4  5831.4  5921.4  6081.4  6151.4  6211.4  6221.4
   132.9   132.2     132   130.1   128.7   128.6   130.4   130.7   130.4   130.6
  130.43  130.43  131.03  130.43  130.31  129.83  129.53  129.47  129.47  133.97
  133.97  134.47  135.88   135.7  133.97  133.97  129.47  128.84  126.97  127.67
  127.36   127.8  128.32  127.71  129.47  130.01  130.55  132.44  133.13  133.48
     132     131     131     129     128     128     129     130     129     130
     129     129     130     129     129     128     128     126     126     126
  126.57     127  128.41  128.23   126.5     120     120     120     120     120
     120     120     120     120     120     120     120     120     120     120
BR Coef= 1 , 1 , 0 ,1.25, 0 ,,,0.8,0,2,0,
WSPro=,,,, 1 ,,,, 0 ,,,, 0 ,,,,-1 ,-1 ,-1 , 0 , 0 , 0 , 0 , 0
BC Design=,, 0 ,, 0 ,,,,,,
BC HTab HWMax=134
BC Use User HTab Curves=0
BC User HTab FreeFlow(D)= 0

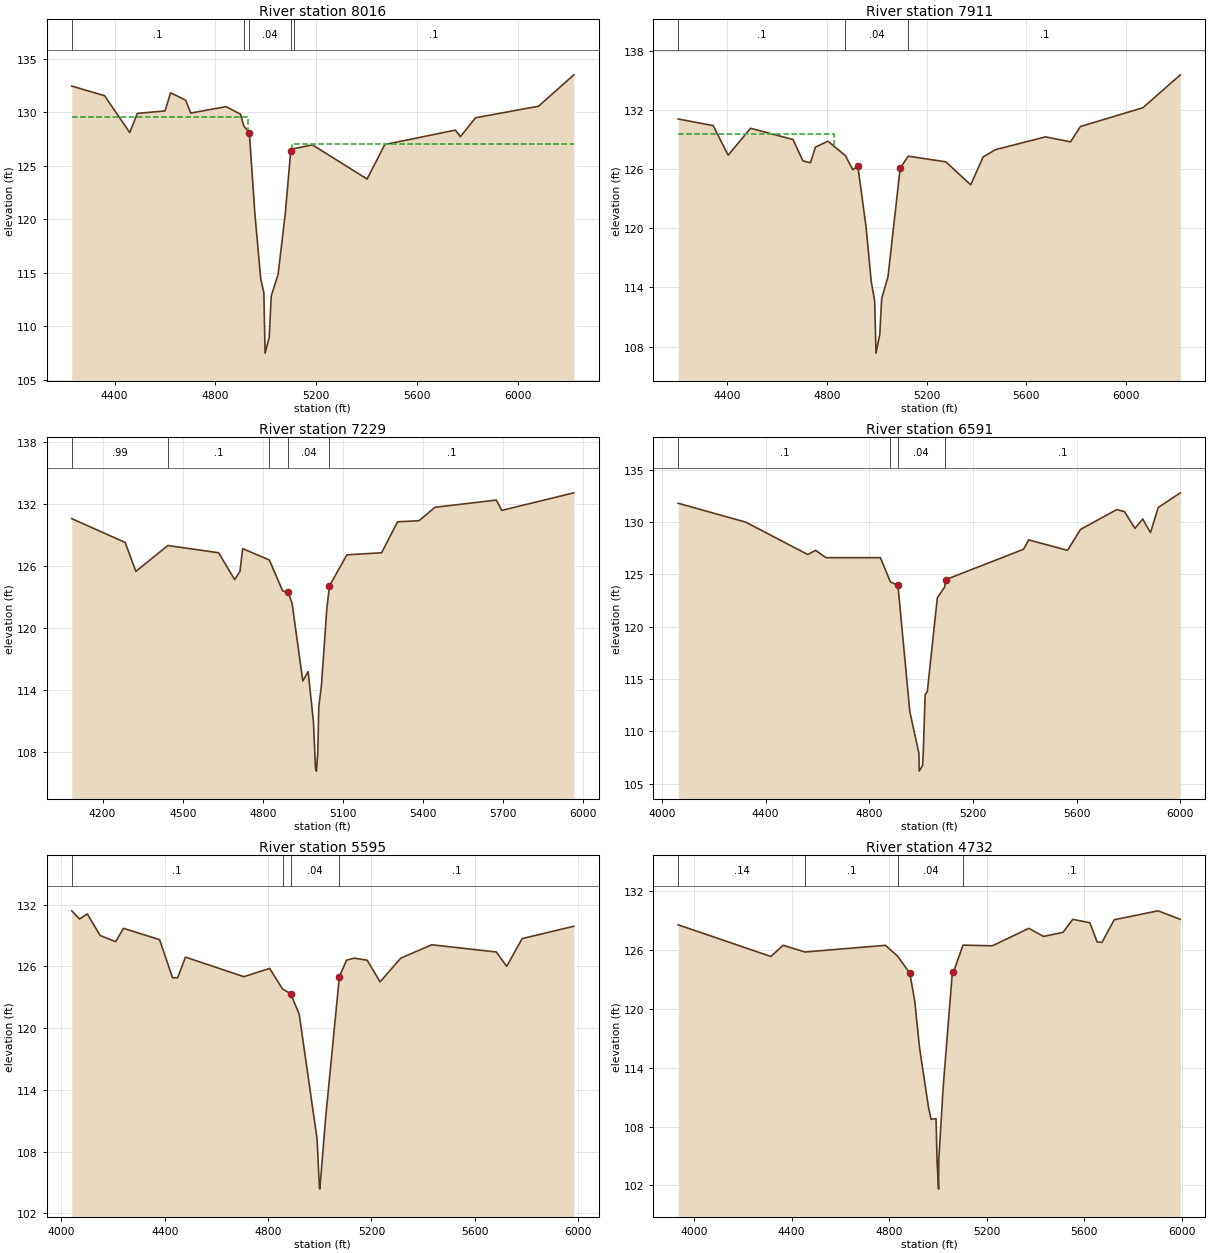
Type RM Length L Ch R = 1 ,8016    ,107,105,93
BEGIN DESCRIPTION:
K142-00-00-S02A_METAL BRIDGR - DS - XS2
END DESCRIPTION:
XS GIS Cut Line= 4
      3044794.58      13924790.6      3044229.92     13924454.62
      3043945.26     13924409.09       3042885.4      13924262.6
#Sta/Elev= 30
  4229.9  132.43  4359.9  131.53  4459.9  128.09  4489.9  129.88  4599.9  130.11
  4621.8  131.81  4681.8  131.11  4701.8  129.91  4841.8  130.51    4899  129.81
  4912.2  128.72  4934.3  128.07  4956.3  120.49  4979.3  114.45  4991.8  113.15
  4996.7   107.5  5013.1  108.97  5021.1  112.84  5048.3  114.85    5077  120.57
  5098.4  126.36  5111.1  126.59 5184.49  126.94  5401.4  123.75  5471.4  126.97
  5751.4  128.32  5771.4  127.71  5831.4  129.47  6081.4  130.55  6221.4  133.48
#Mann= 5 ,-1 , 0
  4229.9      .1       0  4912.2    .045       0  4934.3     .04       0
  5098.4    .045       0  5111.1      .1       0
#XS Ineff= 2 , 0
       0 4927.63  129.53 5105.07       0     127
Permanent Ineff=
       F       F
Bank Sta=4934.3,5098.4
XS Rating Curve= 0 ,0
Exp/Cntr=0.5,0.3

Type RM Length L Ch R = 1 ,7911    ,575.1,682,746.2
BEGIN DESCRIPTION:
K142-00-00-S02A_METAL BRIDGR - DS - XS1
END DESCRIPTION:
XS GIS Cut Line= 4
      3044785.91      13924686.4      3044123.98     13924327.83
      3043994.43     13924325.64      3042876.72     13924158.45
#Sta/Elev= 30
  4204.5  131.07  4344.5   130.4  4404.5   127.4  4494.5  130.13  4664.5  128.99
  4704.5  126.82  4734.5  126.64  4754.5  128.22  4804.5  128.82  4874.5  127.36
  4904.5  125.92  4924.5  126.29  4957.4  120.12 4978.27  114.57  4991.9  112.64
 4997.24  107.33 5012.55  109.27 5020.02  112.86 5045.41  115.08 5094.23  126.11
  5126.9   127.3  5276.9  126.73  5376.9   124.4  5426.9  127.23  5476.9  127.97
  5676.9  129.26  5776.9  128.75  5816.9  130.31  6066.9  132.21  6217.1  135.55
#Mann= 3 ,-1 , 0
  4204.5      .1       0  4874.5     .04       0  5126.9      .1       0
#XS Ineff= 2 , 0
       0 4827.63  129.53 5205.07       0     127
Permanent Ineff=
       F       F
Bank Sta=4924.5,5094.23
XS Rating Curve= 0 ,0
Exp/Cntr=0.3,0.1

Type RM Length L Ch R = 1 ,7229    ,671.9,638,617.3
BEGIN DESCRIPTION:
Cross Section K142-00-00-X4
END DESCRIPTION:
XS GIS Cut Line= 5
      3044930.59      13924561.2 3044804.014799113924406.3552982
      3044408.33     13923922.28      3044389.73     13923738.11
      3043920.58      13923005.4
#Sta/Elev= 30
  4084.6   130.6  4284.6   128.3  4324.6   125.5  4444.6     128  4634.6   127.3
  4694.6   124.7  4714.6   125.5  4724.6   127.7  4824.6   126.6  4874.6   123.6
  4894.6   123.5  4909.8   122.4  4949.8   114.9  4969.8   115.8  4989.8   110.9
  4997.3  106.44  5000.9  106.17  5005.7  107.87  5009.8   112.4  5019.8   114.5
  5039.8   121.9  5049.8   124.1  5114.9   127.1  5244.9   127.3  5304.9   130.3
  5384.9   130.4  5444.9   131.7  5674.9   132.4  5694.9   131.4  5964.9   133.1
#Mann= 5 ,-1 , 0
  4084.6     .99       0  4444.6      .1       0  4824.6    .045       0
  4894.6     .04       0  5049.8      .1       0
Bank Sta=4894.6,5049.8
XS Rating Curve= 0 ,0
Exp/Cntr=0.3,0.1

Type RM Length L Ch R = 1 ,6591    ,924.2,996,1032.9
BEGIN DESCRIPTION:
Cross Section K142-00-00-X3
END DESCRIPTION:
XS GIS Cut Line= 4
      3045515.66      13924390.8      3045042.09     13923698.82
      3044955.69     13923560.91      3044422.58      13922792.7
#Sta/Elev= 30
  4062.9   131.8  4322.9     130  4562.9   126.9  4592.9   127.3  4632.9   126.6
  4842.9   126.6  4881.5  124.28  4910.5  123.96  4956.4  111.88  4991.5   107.9
  4992.4  106.19  5005.6  106.74  5008.4  108.05  5015.5   113.5    5024  113.82
  5062.5  122.76  5090.6  123.79  5092.9  124.16    5095   124.5    5395   127.4
    5415   128.3    5565   127.3    5615   129.3  5754.9   131.2  5784.9     131
  5824.9   129.4  5854.9   130.3  5884.9     129  5914.9   131.4    6000   132.8
#Mann= 5 ,-1 , 0
  4062.9      .1       0  4881.5    .045       0  4910.5     .04       0
  5090.6     .04       0  5092.9      .1       0
Bank Sta=4910.5,5095
XS Rating Curve= 0 ,0
Exp/Cntr=0.3,0.1

Type RM Length L Ch R = 1 ,5595    ,895.7,863,797.9
BEGIN DESCRIPTION:
Cross Section K142-00-00-X2
END DESCRIPTION:
XS GIS Cut Line= 4
      3045922.13       13924466.      3045913.19     13923604.54
      3045956.77     13923428.06       3045918.4      13922528.8
#Sta/Elev= 30
  4039.8   131.4  4069.8   130.6  4099.8   131.1  4149.8     129  4209.8   128.4
  4239.8   129.7  4379.8   128.6  4429.8   124.9  4449.8   124.9  4479.8   126.9
  4705.8     125  4805.8   125.8  4855.8   123.8  4886.7  123.36  4920.2  121.36
  4989.3  109.24  4998.5  104.43  5000.1  104.35  5022.4  111.25  5075.6  124.99
  5103.3   126.6  5133.3   126.8  5183.3   126.6  5233.3   124.5  5313.3   126.8
  5433.3   128.1  5683.3   127.4  5723.3     126  5783.3   128.7  5983.3   129.9
#Mann= 4 ,-1 , 0
  4039.8      .1       0  4855.8    .045       0  4886.7     .04       0
  5075.6      .1       0
Bank Sta=4886.7,5075.6
XS Rating Curve= 0 ,0
Exp/Cntr=0.3,0.1

Type RM Length L Ch R = 1 ,4732    ,104.3,105,113.7
BEGIN DESCRIPTION:
K142-00-00-S2B_PL - US - XS4
END DESCRIPTION:
XS GIS Cut Line= 4
       3046633.2      13924278.9      3046694.87     13923277.32
      3046646.52     13923162.32      3046236.57     13922326.21
#Sta/Elev= 30
  3934.7  128.58  4314.7  125.35  4364.7  126.49  4454.7  125.81  4784.7  126.49
  4834.7  125.38  4884.7  123.64  4904.7  120.82  4924.7  116.01 4960.95  110.01
 4971.77  108.73  4992.3  108.81 4996.54  104.38 5002.61  101.61 5003.34  104.55
 5021.86  112.15  5058.3  123.49    5063  123.73    5103  126.51    5223  126.44
    5373  128.22    5433   127.4    5513  127.81    5553  129.14    5623   128.8
    5653  126.83    5673  126.79    5723   129.1    5903  130.01  5994.2  129.14
#Mann= 4 ,-1 , 0
  3934.7     .14       0  4454.7      .1       0  4834.7     .04       0
    5103      .1       0
#XS Ineff= 2 , 0
       0    4790     125    5165       0  120.94
Permanent Ineff=
       F       F
Bank Sta=4884.7,5063
XS Rating Curve= 0 ,0
Exp/Cntr=0.5,0.3

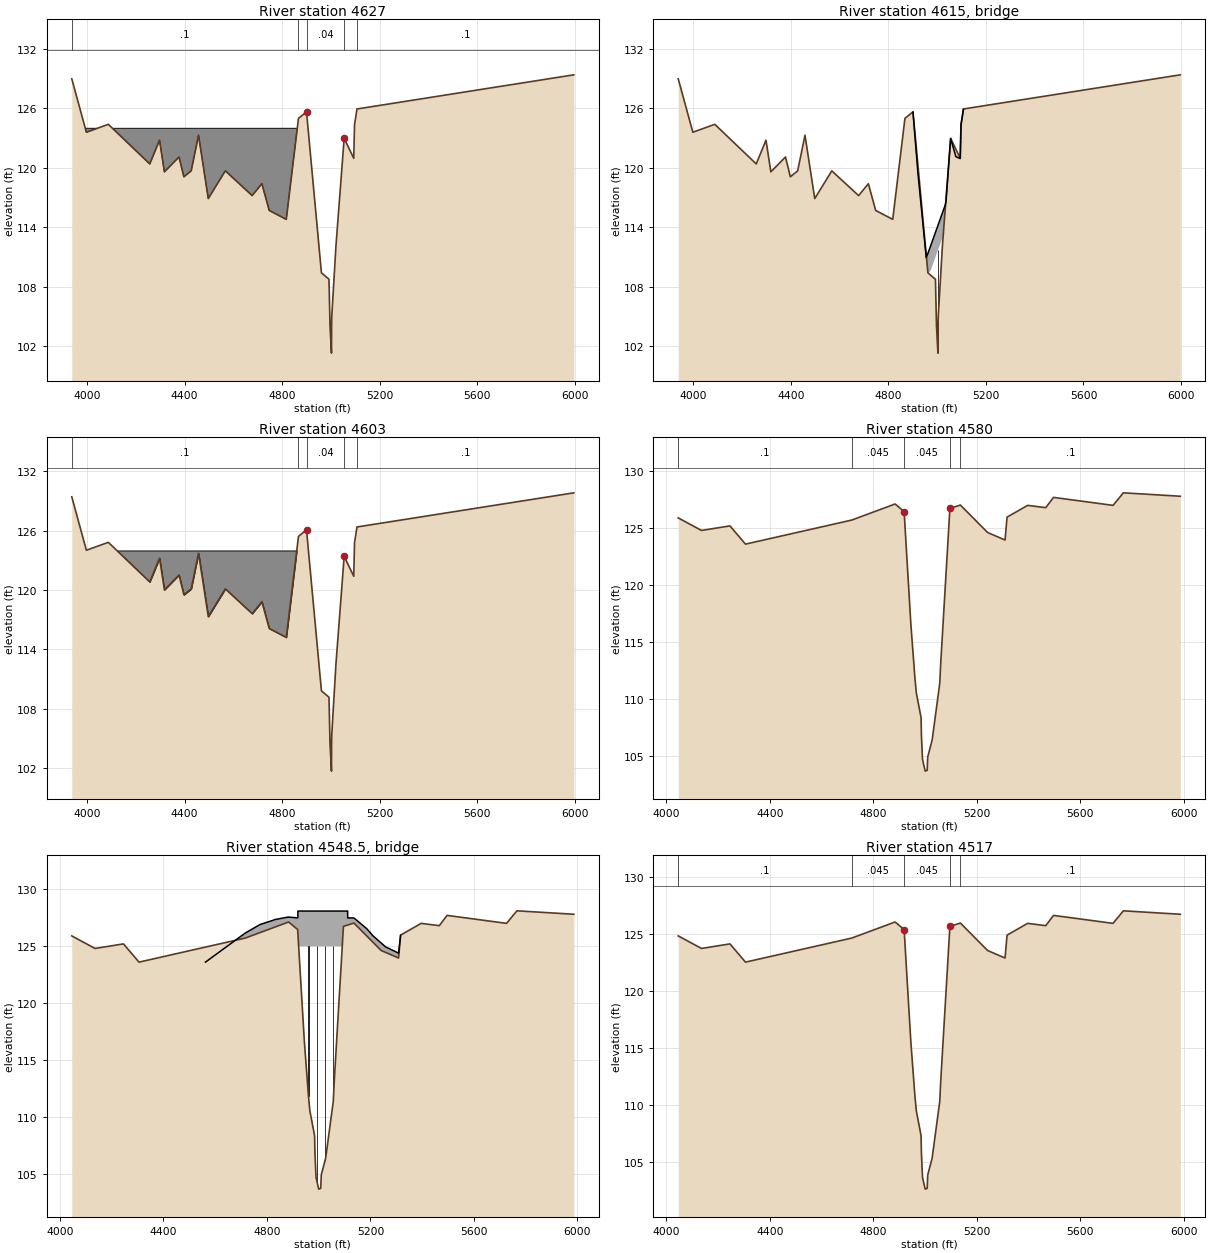
Type RM Length L Ch R = 1 ,4627    ,23.8,24,24.9
BEGIN DESCRIPTION:
K142-00-00-S2B_PL - US - XS3
END DESCRIPTION:
XS GIS Cut Line= 4
      3046728.68      13924248.6      3046785.23     13923284.43
      3046761.68     13923143.13      3046332.05      13922295.8
#Sta/Elev= 30
  3937.5     129  3997.5   123.6  4087.5   124.4  4257.5   120.4  4297.5   122.8
  4317.5   119.6  4377.5   121.1  4397.5   119.1  4427.5   119.7  4457.5   123.3
  4497.5   116.9  4567.5   119.7  4677.5   117.2  4717.5   118.4  4747.5   115.7
  4817.5   114.8  4867.5     125  4900.5  125.66  4961.7   109.4  4992.7  108.75
  4996.9  104.07  5002.9  101.29  5003.6  104.57  5004.5  105.12  5021.3  112.13
    5055  122.99  5094.3  120.97  5097.5  124.36  5107.5  125.95  5997.2   129.4
#Mann= 5 ,-1 , 0
  3937.5      .1       0  4867.5    .045       0  4900.5     .04       0
    5055    .045       0  5107.5      .1       0
#XS Ineff= 2 , 0
       0  4890.5     125    5065       0  120.94
Permanent Ineff=
       F       F
#Block Obstruct= 2 , 0
       0    4880     124               0
Bank Sta=4900.5,5055
XS Rating Curve= 0 ,0
Exp/Cntr=0.5,0.3

Type RM Length L Ch R = 3 ,4615    ,,,
BEGIN DESCRIPTION:
PL1_K142-00-00-S2B
END DESCRIPTION:
Bridge Culvert--1,0,-1,-1, 0
Deck Dist Width WeirC Skew NumUp NumDn MinLoCord MaxHiCord MaxSubmerge Is_Ogee
10,3,2.6,0, 31, 31, , , 0.95, 0, ,,,
  4900.5  4920.7 4954.84  4955.8  4961.7  4962.8 4962.91    4963  4963.2  4972.4
  4992.7  4995.4  4996.4  4996.9  4999.3  5002.9  5003.5  5003.6  5004.5  5021.3
 5026.42 5032.19  5032.3  5032.4  5035.7  5035.8    5055  5076.7  5094.3  5097.5
  5107.5
  125.63  119.49  110.95     111  111.36  111.43  111.44  111.44  111.46  112.09
  113.49  113.67  113.74  113.78  113.94  114.19  114.23  114.24   114.3  115.45
  115.81   116.2  116.21  116.22  116.54  116.56  122.96  121.13  120.94  124.33
  125.92
  125.63  119.49  110.95  110.73  109.37  109.25  109.23  109.22   109.2  109.59
  110.99  111.17  111.24  111.28  111.44  111.69  111.73  111.74   111.8  112.95
   113.5  115.38  115.42  115.45  116.53  116.56  122.96  121.13  120.94  124.33
  125.92
  4900.5  4920.7 4954.84  4955.8  4961.7  4962.8 4962.91    4963  4963.2  4972.4
  4992.7  4995.4  4996.4  4996.9  4999.3  5002.9  5003.5  5003.6  5004.5  5021.3
 5026.42 5032.19  5032.3  5032.4  5035.7  5035.8    5055  5076.7  5094.3  5097.5
  5107.5
  125.63  119.49  110.95     111  111.36  111.43  111.44  111.44  111.46  112.09
  113.49  113.67  113.74  113.78  113.94  114.19  114.23  114.24   114.3  115.45
  115.81   116.2  116.21  116.22  116.54  116.56  122.96  121.13  120.94  124.33
  125.92
  125.63  119.49  110.95  110.73  109.37  109.25  109.23  109.22   109.2  109.59
  110.99  111.17  111.24  111.28  111.44  111.69  111.73  111.74   111.8  112.95
   113.5  115.38  115.42  115.45  116.53  116.56  122.96  121.13  120.94  124.33
  125.92
Pier Skew, UpSta & Num, DnSta & Num=  ,5002.9, 2 ,5002.9, 2 , 0 , 0 , 0 ,,
     1.1     1.1
   100.5  112.73
     1.1     1.1
  100.51  112.74
BR Coef= 1 , 1 , 1 ,1.25, 0 ,,,0.8,0,2,0,
WSPro=,,,, 1 ,,,, 0 ,,,, 0 ,,,,-1 ,-1 ,-1 , 0 , 0 , 0 , 0 , 0
BR D #Sta/Elev= 101
  3937.5     129  3957.5   128.4  3967.5   127.6  3977.5   125.3  3987.5   124.2
  3997.5   123.6  4007.5   124.1  4027.5   123.3  4067.5   123.6  4087.5   124.4
  4127.5   122.8  4157.5     123  4187.5     122  4207.5     122  4217.5   121.1
  4237.5     121  4257.5   120.4  4267.5   120.4  4297.5   122.8  4307.5   120.6
  4317.5   119.6  4327.5   119.3  4337.5   119.6  4347.5   119.6  4367.5   120.3
  4377.5   121.1  4397.5   119.1  4417.5   119.2  4427.5   119.7  4437.5   121.2
  4457.5   123.3  4467.5   121.8  4477.5   119.4  4487.5   117.6  4497.5   116.9
  4507.5   116.9  4517.5   118.3  4537.5   118.4  4547.5   119.5  4567.5   119.7
  4587.5   118.9  4597.5   118.9  4607.5   117.9  4617.5   118.6  4627.5   118.9
  4677.5   117.2  4687.5   117.4  4697.5   117.2  4717.5   118.4  4747.5   115.7
  4767.5   115.1  4787.5   115.6  4807.5   115.5  4817.5   114.8  4827.5   115.9
  4837.5   118.8  4847.5   120.5  4867.5     125  4877.5     126  4897.5   126.1
  4900.5  125.66  4920.7  119.52 4954.84  110.98  4955.8  110.76  4961.7   109.4
  4962.8  109.28 4962.91  109.26    4963  109.25  4963.2  109.23  4972.4  108.21
  4992.7  108.75  4995.4  106.23  4996.4  104.77  4996.9  104.07  4999.3  102.85
  5002.9  101.29  5003.5  104.28  5003.6  104.57  5004.5  105.12  5021.3  112.13
 5026.42  113.53 5032.19  115.41  5032.3  115.45  5032.4  115.48  5035.7  116.56
  5035.8  116.59    5055  122.99  5076.7  121.16  5094.3  120.97  5097.5  124.36
  5107.5  125.95  5117.5  126.53  5227.5  126.74  5247.5  126.36  5407.2   128.5
  5647.2   128.1  5677.2   127.4  5737.2   129.2  5807.2   129.5  5857.2   129.3
  5997.2   129.4
BR D #Mann= 5
  3937.5      .1  4867.5    .045  4900.5     .04    5055    .045  5107.5      .1
BC Design=,, 0 ,, 0 ,,,,,,
BC HTab HWMax=129.5
BC Use User HTab Curves=0
BC User HTab FreeFlow(D)= 0

Type RM Length L Ch R = 1 ,4603    ,11.8,23,37.7
BEGIN DESCRIPTION:
K142-00-00-S2B_PL - DS - XS2
END DESCRIPTION:
XS GIS Cut Line= 4
      3046756.88      13924248.5      3046809.02     13923283.89
      3046783.81     13923132.58      3046394.87    13922283.674
#Sta/Elev= 30
  3937.5  129.42  3997.5  124.02  4087.5  124.82  4257.5  120.82  4297.5  123.22
  4317.5  120.02  4377.5  121.52  4397.5  119.52  4427.5  120.12  4457.5  123.72
  4497.5  117.32  4567.5  120.12  4677.5  117.62  4717.5  118.82  4747.5  116.12
  4817.5  115.22  4867.5  125.42  4900.5  126.08  4961.7  109.82  4992.7  109.17
  4996.9  104.49  5002.9  101.71  5003.6  104.99  5004.5  105.54  5021.3  112.55
    5055  123.41  5094.3  121.39  5097.5  124.78  5107.5  126.37  5997.2  129.82
#Mann= 5 ,-1 , 0
  3937.5      .1       0  4867.5    .045       0  4900.5     .04       0
    5055    .045       0  5107.5      .1       0
#XS Ineff= 2 , 0
       0 4893.83     125 5061.67       0  121.36
Permanent Ineff=
       F       F
#Block Obstruct= 2 , 0
       0    4880     124               0
Bank Sta=4900.5,5055
XS Rating Curve= 0 ,0
Exp/Cntr=0.5,0.3

Type RM Length L Ch R = 1 ,4580    ,60.2,63,65.4
BEGIN DESCRIPTION:
K142-00-00-S2_LAKEWOOD FOREST DR - US - XS3
END DESCRIPTION:
XS GIS Cut Line= 5
      3046924.49       13924111.      3046815.32     13923943.76
      3046812.36     13923446.97      3046819.94     13922983.33
      3046497.91      13922272.9
#Sta/Elev= 30
  4045.6   125.9  4135.6   124.8  4245.5   125.2  4305.5   123.6  4716.2  125.71
  4883.7  127.12  4918.6  126.46  4944.6   116.6  4960.2  111.89  4965.6  110.58
  4984.1  108.38  4985.5  106.81  4989.7  104.71    5000  103.69  5007.7  103.76
  5009.9  104.94    5027  106.42  5056.4  111.41  5059.9   113.1  5095.5  126.73
    5136  127.03  5241.2  124.62  5308.6  123.96  5316.5  125.97    5396     127
    5466   126.8    5496   127.7    5726     127    5766   128.1    5986   127.8
#Mann= 5 ,-1 , 0
  4045.6      .1       0  4716.2    .045       0  4918.6    .045       0
  5095.5    .045       0    5136      .1       0
#XS Ineff= 2 , 0
       0  4908.6   123.6  5105.5       0  124.39
Permanent Ineff=
       F       F
Bank Sta=4918.6,5095.5
XS Rating Curve= 0 ,0
Exp/Cntr=0.5,0.3

Type RM Length L Ch R = 3 ,4548.5  ,,,
BEGIN DESCRIPTION:
LAKEWOOD FOREST DR.
Structure ID: K142-00-00-S2
END DESCRIPTION:
Bridge Culvert--1,0,-1,-1, 0
Deck Dist Width WeirC Skew NumUp NumDn MinLoCord MaxHiCord MaxSubmerge Is_Ogee
10,40,2.6,0, 49, 49, , , 0.95, 0, ,,,
  4562.2  4702.8  4716.2  4771.7  4772.1  4826.4  4829.8  4883.7  4884.2  4918.6
 4919.29  4919.4 4919.51 4923.31  4923.4  4923.5  4928.5  4935.4  4944.6  4960.2
  4965.6  4984.1  4985.5  4989.7    4991  4992.7    5000  5007.7  5009.9    5027
  5042.4  5056.4  5059.9  5088.1 5089.45 5089.59  5089.7  5095.5 5111.79  5111.9
 5112.01    5136  5154.3  5185.9    5210  5241.2  5258.2  5308.6  5316.5
   123.6  125.93  126.15  126.88  126.89  127.29  127.33  127.56  127.55  127.48
  127.48  128.08  128.08  128.08  128.08  128.08  128.08  128.08  128.08  128.08
  128.08  128.08  128.08  128.08  128.08  128.08  128.08  128.08  128.08  128.08
  128.08  128.08  128.08  128.08  128.08  128.08  128.08  128.08  128.08  128.08
  127.48  127.47  127.13  126.53   125.9  125.28  124.94  124.39  125.97
   123.6     124     124     124     124     124     124     124     124     124
     124     124  124.98  124.98  124.98  124.98  124.98  124.98  124.98  124.98
  124.98  124.98  124.98  124.98  124.98  124.98  124.98  124.98  124.98  124.98
  124.98  124.98  124.98  124.98  124.98  124.98  124.98  124.98     124     124
     124     124     124     124     124     124     124     123     123
  4562.2  4702.8  4716.2  4771.7  4772.1  4826.4  4829.8  4883.7  4884.2  4918.6
 4919.29  4919.4 4919.51 4923.31  4923.4  4923.5  4928.5  4935.4  4944.6  4960.2
  4965.6  4984.1  4985.5  4989.7    4991  4992.7    5000  5007.7  5009.9    5027
  5042.4  5056.4  5059.9  5088.1 5089.45 5089.59  5089.7  5095.5 5111.79  5111.9
 5112.01    5136  5154.3  5185.9    5210  5241.2  5258.2  5308.6  5316.5
   123.6  125.93  126.15  126.88  126.89  127.29  127.33  127.56  127.55  127.48
  127.48  128.08  128.08  128.08  128.08  128.08  128.08  128.08  128.08  128.08
  128.08  128.08  128.08  128.08  128.08  128.08  128.08  128.08  128.08  128.08
  128.08  128.08  128.08  128.08  128.08  128.08  128.08  128.08  128.08  128.08
  127.48  127.47  127.13  126.53   125.9  125.28  124.94  124.39  124.93
  122.12  124.44  124.66  125.18  125.18   125.8  125.84  126.07  126.06  125.41
  125.14   125.1  125.06  123.57  123.54   123.5   123.5   123.5   123.5   123.5
   123.5   123.5   123.5   123.5   123.5   123.5   123.5   123.5   123.5   123.5
   123.5   123.5   123.5   123.5   123.5  123.55  123.59  125.68   125.8   125.8
   125.8  125.98  125.64  125.04   124.4  123.57   123.4  122.91  124.93
Pier Skew, UpSta & Num, DnSta & Num=  ,4960.2, 2 ,4960.2, 2 , 0 , 0 , 0 ,,
     1.2     1.2
  111.17  125.98
     1.2     1.2
  109.69   124.5
Pier Skew, UpSta & Num, DnSta & Num=  ,4992.8, 2 ,4992.8, 2 , 0 , 0 , 0 ,,
     1.2     1.2
  103.64  125.98
     1.2     1.2
  102.16   124.5
Pier Skew, UpSta & Num, DnSta & Num=  ,5024.3, 2 ,5024.3, 2 , 0 , 0 , 0 ,,
     1.2     1.2
  105.56  125.98
     1.2     1.2
  104.08   124.5
Pier Skew, UpSta & Num, DnSta & Num=  ,5056.4, 2 ,5056.4, 2 , 0 , 0 , 0 ,,
     1.2     1.2
  110.74  125.98
     1.2     1.2
  109.26   124.5
BR Coef= 1 , 1 , 1 ,1.25, 0 ,,,0.8,0,2,0,
WSPro=,,,, 1 ,,,, 0 ,,,, 0 ,,,,-1 ,-1 ,-1 , 0 , 0 , 0 , 0 , 0
BC Design=,, 0 ,, 0 ,,,,,,
BC HTab HWMax=128.1
BC Use User HTab Curves=0
BC User HTab FreeFlow(D)= 0

Type RM Length L Ch R = 1 ,4517    ,124.6,103,72.6
BEGIN DESCRIPTION:
K142-00-00-S2_LAKEWOOD FOREST DR - DS - XS2
END DESCRIPTION:
XS GIS Cut Line= 5
        3046965.      13924060.5       3046867.4     13923909.03
      3046867.81     13923422.85      3046875.45     13922955.42
      3046551.18      13922238.8
#Sta/Elev= 30
  4045.6  124.86  4135.6  123.76  4245.5  124.16  4305.5  122.56  4716.2  124.67
  4883.7  126.08  4918.6  125.42  4944.6  115.56  4960.2  110.85  4965.6  109.54
  4984.1  107.34  4985.5  105.77  4989.7  103.67    5000  102.65  5007.7  102.72
  5009.9   103.9    5027  105.38  5056.4  110.37  5059.9  112.06  5095.5  125.69
    5136  125.99  5241.2  123.58  5308.6  122.92  5316.5  124.93    5396  125.96
    5466  125.76    5496  126.66    5726  125.96    5766  127.06    5986  126.76
#Mann= 5 ,-1 , 0
  4045.6      .1       0  4716.2    .045       0  4918.6    .045       0
  5095.5    .045       0    5136      .1       0
#XS Ineff= 2 , 0
       0  4908.6  122.56  5105.5       0  123.35
Permanent Ineff=
       F       F
Bank Sta=4918.6,5095.5
XS Rating Curve= 0 ,0
Exp/Cntr=0.5,0.3

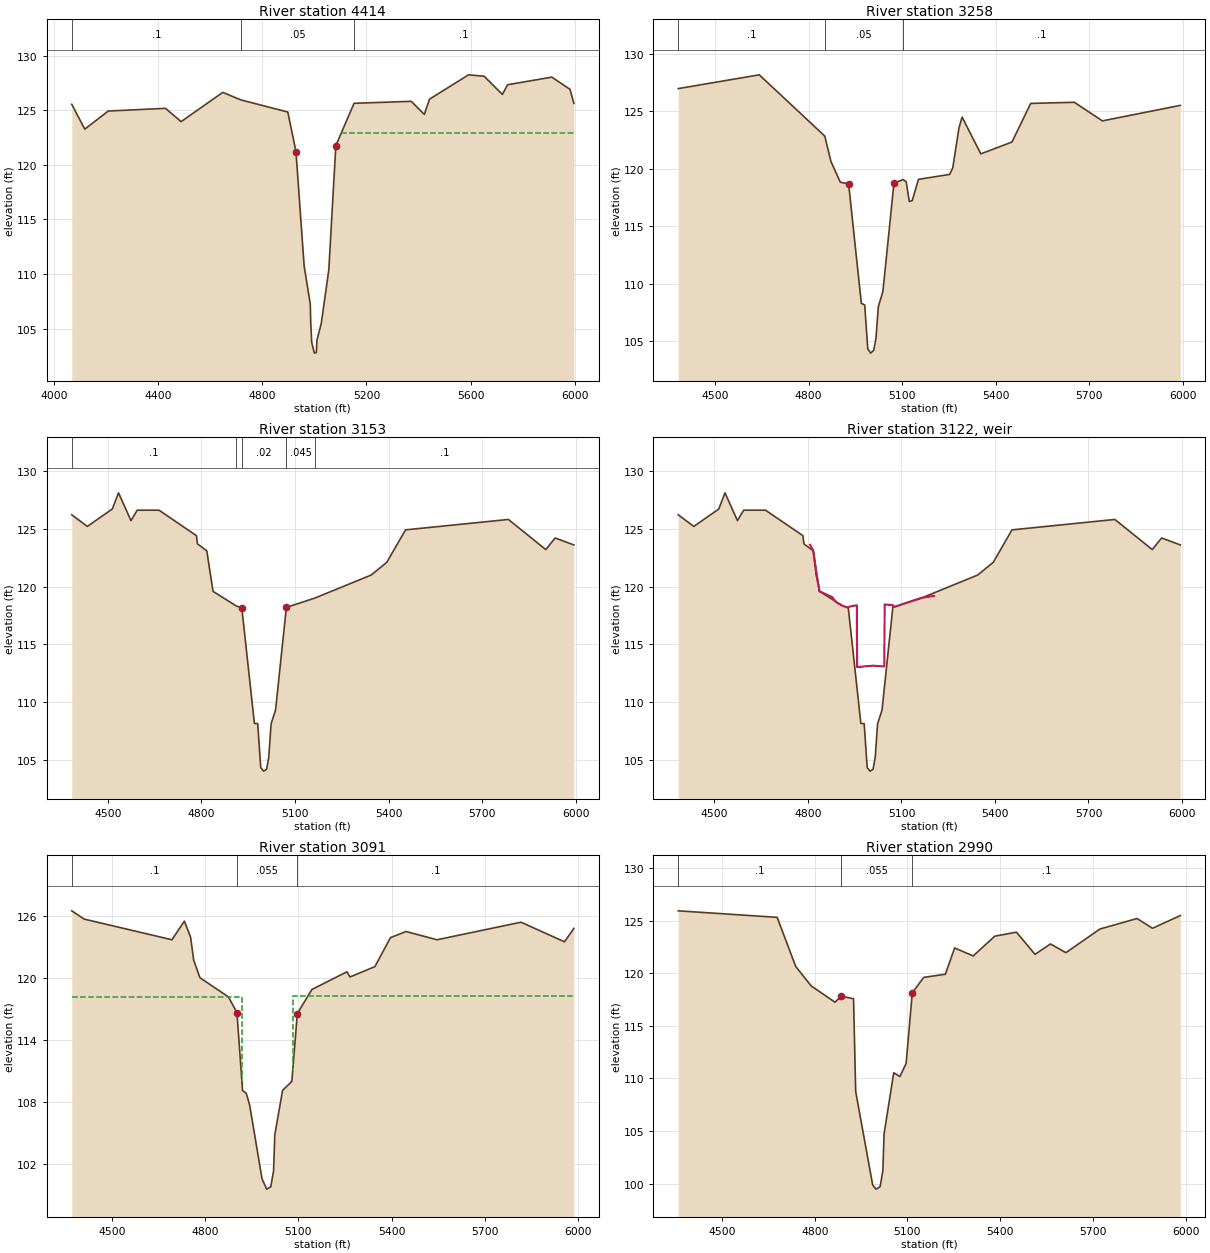
Type RM Length L Ch R = 1 ,4414    ,1157.3,1156,1094.3
BEGIN DESCRIPTION:
K142-00-00-S2_LAKEWOOD FOREST DR - DS - XS1
END DESCRIPTION:
XS GIS Cut Line= 5
      3047058.32      13924017.1      3046960.71     13923865.63
      3046986.29     13923166.24      3046934.02     13923042.09
      3046759.45     13922144.31
#Sta/Elev= 30
  4067.6  125.56  4117.6  123.28  4207.6  124.94  4427.8  125.19  4487.8  123.97
  4647.8  126.65  4717.8  125.96  4897.8  124.85 4929.19  121.22 4960.56  110.74
 4984.21  107.25 4985.59  105.77 4989.75  103.72 4999.94  102.75 5007.51  102.82
 5009.67  103.92 5026.34  105.47 5055.38  110.39  5082.4  121.77  5152.4  125.65
  5372.4  125.83  5422.4  124.63  5442.4  126.03  5592.4  128.26  5652.4  128.13
  5722.4  126.46  5742.4  127.35  5912.4  128.05  5982.4  126.93    5997  125.65
#Mann= 3 ,-1 , 0
  4067.6      .1       0  4717.8     .05       0  5152.4      .1       0
#XS Ineff= 2 , 0
        4909.399 122.2365103.784        122.9706
Permanent Ineff=
       F       F
Bank Sta=4929.19,5082.4
XS Rating Curve= 0 ,0
Exp/Cntr=0.3,0.1

Type RM Length L Ch R = 1 ,3258    ,104.5,105,117
BEGIN DESCRIPTION:
K142-00-00-S01A_WEIR - US - XS4
END DESCRIPTION:
XS GIS Cut Line= 4
      3048326.65      13923630.9      3048102.26     13923149.41
      3047995.32     13922957.78      3047508.04     13922249.19
#Sta/Elev= 30
    4382  126.99    4642  128.19    4852  122.86    4872  120.64    4902  118.84
 4928.61   118.7  4969.4   108.3 4980.23  108.15 4990.05  104.33 4999.26  103.96
 5009.17  104.21 5016.33  105.25  5023.9  107.99 5038.62  109.34 5073.99  118.75
  5103.3  119.07  5113.3  118.88  5123.3  117.16  5132.7  117.24  5152.7  119.09
  5252.7  119.52  5262.7  120.09  5282.7  123.58  5292.7  124.51  5352.7  121.31
  5452.7  122.34  5512.7   125.7  5652.7   125.8  5742.7  124.18  5992.7  125.53
#Mann= 3 ,-1 , 0
    4382      .1       0    4852     .05       0  5103.3      .1       0
#XS Ineff= 2 , 0
        4918.614118.49885083.989        118.5934
Permanent Ineff=
       F       F
Bank Sta=4928.61,5073.99
XS Rating Curve= 0 ,0
Exp/Cntr=0.7,0.5

Type RM Length L Ch R = 1 ,3153    ,65.7,62,59
BEGIN DESCRIPTION:
K142-00-00-S01A_WEIR - US - XS3
END DESCRIPTION:
XS GIS Cut Line= 4
       3048417.8      13923578.8       3048193.4     13923097.33
      3048086.47     13922905.69 3047599.185358613922197.1030574
#Sta/Elev= 30
  4383.9   126.2  4433.9   125.2  4513.9   126.7  4533.9   128.1  4573.9   125.7
  4593.9   126.6  4663.9   126.6  4783.9   124.4  4787.1  123.69  4817.1  123.09
  4837.1  119.59  4912.2  118.32  4929.4  118.17  4969.8  108.18  4980.4  108.16
  4990.1  104.37  4999.2  104.06  5008.9  104.22  5015.9  105.27  5023.3  108.14
  5037.7  109.34  5072.3   118.2  5163.8  119.01  5344.6     121  5394.6   122.1
  5454.6   124.9  5784.6   125.8  5904.6   123.2  5934.6   124.2  5994.6   123.6
#Mann= 5 ,-1 , 0
  4383.9      .1       0  4912.2    .045       0  4929.4     .02       0
  5072.3    .045       0  5163.8      .1       0
#XS Ineff= 2 , 0
       0  4919.4  118.18  5082.3       0  118.22
Permanent Ineff=
       F       F
Bank Sta=4929.4,5072.3
XS Rating Curve= 0 ,0
Exp/Cntr=0.7,0.5

Type RM Length L Ch R = 5 ,3122    ,,,
BEGIN DESCRIPTION:
WIER 400' US JONES RD.
Structure ID: K142-00-00-S01A
END DESCRIPTION:
IW Pilot Flow=0
#Inline Weir SE= 18
  4807.1   123.6  4817.1   123.1  4827.1     121  4837.1   119.6  4877.1   119.1
  4892.1  118.62  4912.2  118.33  4929.4  118.18  4929.7  118.25  4956.7  118.39
  4957.7  113.05  5008.9  113.17    5045   113.1  5046.1  118.46  5072.6   118.4
 5072.71  118.22  5163.8  119.02  5204.3   119.2
IW Dist,WD,Coef,Skew,MaxSub,Min_El,Is_Ogee,SpillHt,DesHd
10,1,3,0,0.95,, 0 ,,,0,0,
Inline Weir Flap Gates= 0

Type RM Length L Ch R = 1 ,3091    ,103,101,99.3
BEGIN DESCRIPTION:
K142-00-00-S01A_WEIR - DS - XS2
Located At: WIER 400' US JONES RD.
END DESCRIPTION:
XS GIS Cut Line= 5
       3048450.2       13923571.      3048342.12     13923236.69
      3048253.78     13923073.26      3048132.06      13922869.8
 3047662.395644813922173.3820013
#Sta/Elev= 30
  4371.4   126.5  4411.4   125.7  4693.6   123.7  4733.6   125.5  4753.6  123.95
  4763.6  121.73  4783.6  120.03  4875.4  118.17  4902.7  116.65  4920.9  109.09
  4932.6  108.86  4943.8  107.68  4983.3  100.58  4998.5   99.57  5011.6    99.8
  5020.6  101.34  5024.4  104.81  5049.5  109.13  5079.3  109.99  5096.9  116.56
  5143.8  118.89  5256.4   120.6  5266.4   120.1  5346.4   121.1  5396.4   123.9
  5446.4   124.5  5546.4   123.7  5816.4   125.4  5956.4   123.5  5986.4   124.8
#Mann= 3 ,-1 , 0
  4371.4      .1       0  4902.7    .055       0  5096.9      .1       0
#XS Ineff= 2 , 0
       0  4919.4  118.18  5082.3       0  118.22
Permanent Ineff=
       F       F
Bank Sta=4902.7,5096.9
XS Rating Curve= 0 ,0
Exp/Cntr=0.7,0.5

Type RM Length L Ch R = 1 ,2990    ,222.1,258,345.5
BEGIN DESCRIPTION:
K142-00-00-S01A_WEIR - DS - XS1
Located At: WIER 400' US JONES RD.
END DESCRIPTION:
XS GIS Cut Line= 4
      3048487.51      13923561.6      3048379.67      13923086.6
      3048225.38      13922832.9      3047755.71      13922136.4
#Sta/Elev= 30
  4358.6  125.94  4678.6  125.32  4738.6  120.65  4788.6   118.8  4865.7  117.25
  4885.7  117.82  4925.7  117.58  4932.6  108.76  4987.7   99.85  4998.5   99.47
  5011.6    99.7  5020.6  101.24  5024.4  104.71  5055.7  110.54  5075.7  110.18
  5095.7  111.42  5115.7  118.14  5152.7  119.61  5222.7  119.91  5252.7  122.41
  5312.7  121.65  5382.7  123.53  5452.7  123.91  5512.7   121.8  5562.7  122.79
  5612.7  121.96  5722.7  124.21  5842.7  125.21  5892.7  124.28  5982.7  125.49
#Mann= 3 ,-1 , 0
  4358.6      .1       0  4885.7    .055       0  5115.7      .1       0
Bank Sta=4885.7,5115.7
XS Rating Curve= 0 ,0
Exp/Cntr=0.5,0.3

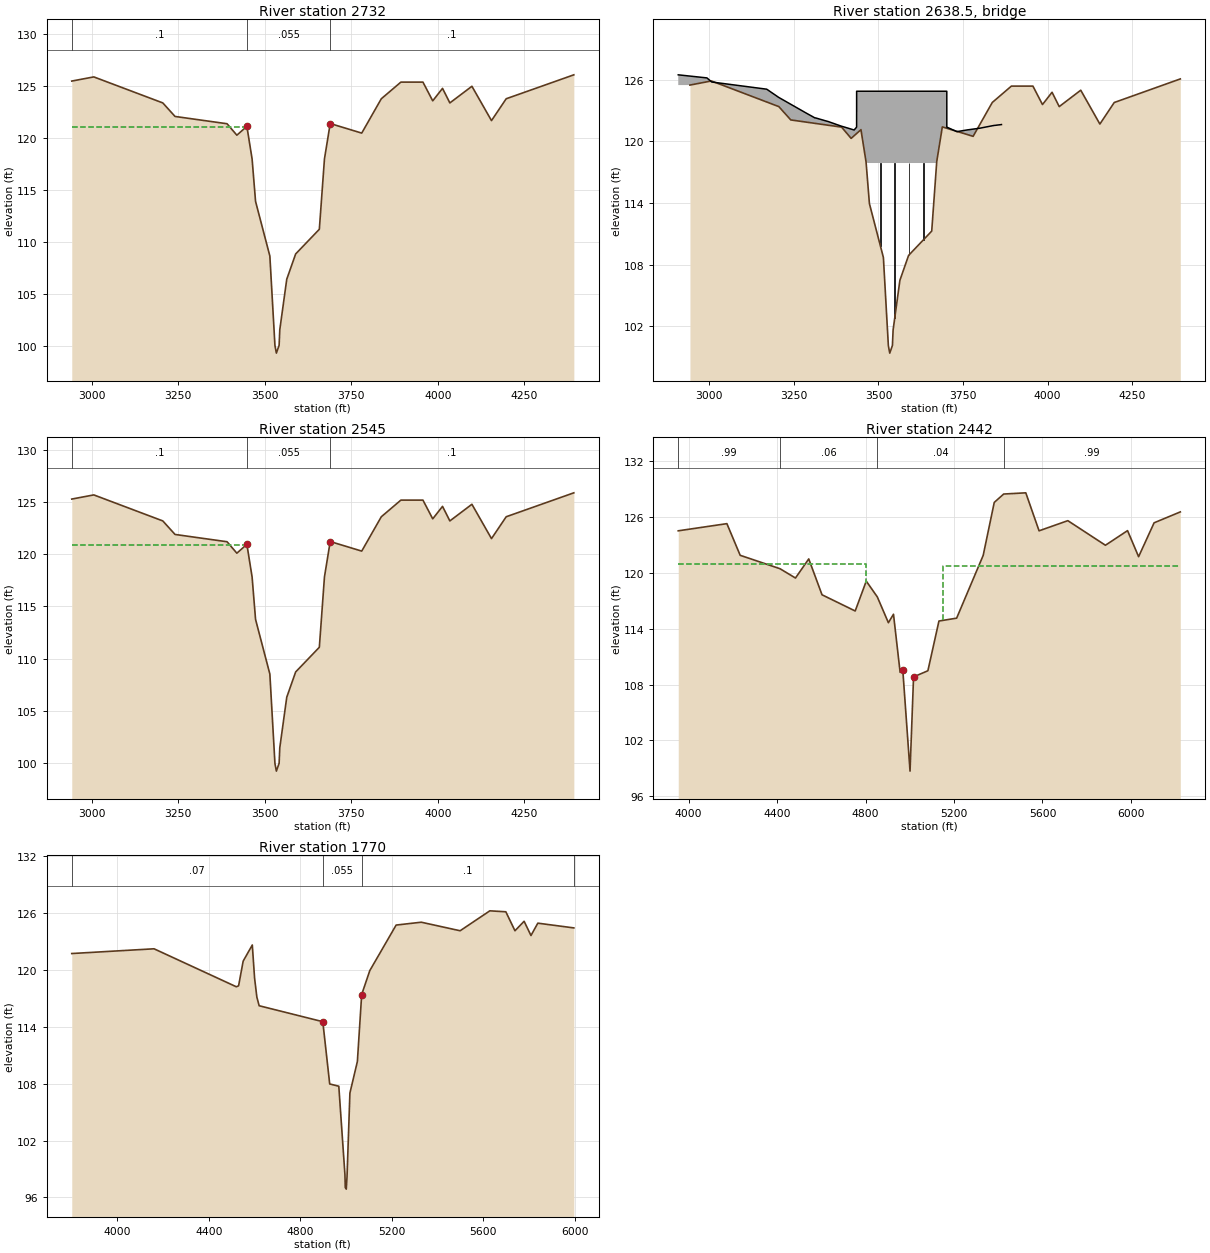
Type RM Length L Ch R = 1 ,2732    ,177.9,187,170.4
BEGIN DESCRIPTION:
K142-00-00-S1_JONES RD - US - XS3
END DESCRIPTION:
XS GIS Cut Line= 5
        3048518.       13923581.      3048531.68     13923250.02
       3048513.5     13922988.19      3048347.49     13922370.08
      3047713.09     13921856.39
#Sta/Elev= 30
2942.625   125.53006.264   125.93205.527   123.43240.882   122.13391.072   121.4
3419.356   120.33448.348  121.153463.409  118.013473.379  113.943514.674  108.69
3529.382  100.093533.483   99.363541.403  100.113543.383  101.613563.465  106.46
3589.202  108.893657.581  111.263672.359  118.023688.976  121.423779.981   120.5
3836.549   123.83893.118   125.43956.758   125.43985.042   123.64013.326   124.8
4034.539   123.4 4098.18     1254154.748   121.74197.174   123.84392.546   126.1
#Mann= 3 ,-1 , 0
2942.625      .1       03448.348    .055       03688.976      .1       0
#XS Ineff= 2 , 0
       03441.277  121.123696.047       0  120.96
Permanent Ineff=
       F       F
Bank Sta=3448.348,3688.976
XS Rating Curve= 0 ,0
Skew Angle= 45
Exp/Cntr=0.5,0.3

Type RM Length L Ch R = 3 ,2638.5  ,,,
BEGIN DESCRIPTION:
JONES ROAD
Structure ID: K142-00-00-S1
END DESCRIPTION:
Bridge Culvert--1,0,-1,-1, 0
Deck Dist Width WeirC Skew NumUp NumDn MinLoCord MaxHiCord MaxSubmerge Is_Ogee
10,142,2.6,45, 61, 61, , , 0.95, 0, ,,,
 2908.12 2992.97 3007.11 3169.75  3205.1 3289.74 3298.02 3312.16    3314 3344.33
 3351.12 3379.41 3388.95 3415.12  3428.2 3435.47 3435.55 3435.63 3448.35 3462.78
 3462.84 3463.41 3463.64 3473.38 3500.04 3503.18 3514.67 3521.25 3527.69 3529.03
 3529.38 3533.48  3541.4 3542.04 3543.38 3563.47  3589.2 3590.97 3624.35 3636.12
 3657.58  3672.1 3672.36 3674.54 3674.62 3674.69 3674.76 3674.84 3680.14 3688.98
 3702.05 3702.13 3702.21 3725.04 3731.97 3762.94  3769.8 3800.98 3809.89 3839.52
 3863.77
   126.5   126.2   125.8   125.1   124.3  122.71  122.56   122.3   122.3  122.01
  121.95  121.62  121.51  121.25  121.12   121.4   124.9   124.9   124.9   124.9
   124.9   124.9   124.9   124.9   124.9   124.9   124.9   124.9   124.9   124.9
   124.9   124.9   124.9   124.9   124.9   124.9   124.9   124.9   124.9   124.9
   124.9   124.9   124.9   124.9   124.9   124.9   124.9   124.9   124.9   124.9
   124.9   124.9   121.4  121.06  120.96  121.13  121.16   121.3  121.36  121.55
  121.65
                                                                                
                                                           117.9   117.9   117.9
   117.9   117.9   117.9   117.9   117.9   117.9   117.9   117.9   117.9   117.9
   117.9   117.9   117.9   117.9   117.9   117.9   117.9   117.9   117.9   117.9
   117.9   117.9   117.9   117.9   117.9   117.9   117.9
                                                                                
        
 2908.12 2992.97 3007.11 3169.75  3205.1 3289.74 3298.02 3312.16    3314 3344.33
 3351.12 3379.41 3388.95 3415.12  3428.2 3435.47 3435.55 3435.63 3448.35 3462.78
 3462.84 3463.41 3463.64 3473.38 3500.04 3503.18 3514.67 3521.25 3527.69 3529.03
 3529.38 3533.48  3541.4 3542.04 3543.38 3563.47  3589.2 3590.97 3624.35 3636.12
 3657.58  3672.1 3672.36 3674.54 3674.62 3674.69 3674.76 3674.84 3680.14 3688.98
 3702.05 3702.13 3702.21 3725.04 3731.97 3762.94  3769.8 3800.98 3809.89 3839.52
 3863.77
   126.5   126.2   125.8   125.1   124.3  122.71  122.56   122.3   122.3  122.01
  121.95  121.62  121.51  121.25  121.12   121.4   124.9   124.9   124.9   124.9
   124.9   124.9   124.9   124.9   124.9   124.9   124.9   124.9   124.9   124.9
   124.9   124.9   124.9   124.9   124.9   124.9   124.9   124.9   124.9   124.9
   124.9   124.9   124.9   124.9   124.9   124.9   124.9   124.9   124.9   124.9
   124.9   124.9   121.4  121.06  120.96  121.13  121.16   121.3  121.36  121.55
  121.65
                                                                                
                                                          117.76  117.76  117.76
  117.76  117.76  117.76  117.76  117.76  117.76  117.76  117.76  117.76  117.76
  117.76  117.76  117.76  117.76  117.76  117.76  117.76  117.76  117.76  117.76
  117.76  117.76  117.76  117.76  117.76  117.76  117.76
                                                                                
        
Pier Skew, UpSta & Num, DnSta & Num=  ,3505.835, 2 ,3505.835, 2 , 0 , 0 , 0 ,,
     1.5     1.5
  108.51   118.9
     1.5     1.5
  108.37  118.76
Pier Skew, UpSta & Num, DnSta & Num=  ,3548.19, 2 ,3548.19, 2 , 0 , 0 , 0 ,,
     1.5     1.5
  101.63   118.9
     1.5     1.5
  101.49  118.76
Pier Skew, UpSta & Num, DnSta & Num=  ,3590.971, 2 ,3590.971, 2 , 0 , 0 , 0 ,,
     1.5     1.5
  107.82   118.9
     1.5     1.5
  107.68  118.76
Pier Skew, UpSta & Num, DnSta & Num=  ,3633.468, 2 ,3633.468, 2 , 0 , 0 , 0 ,,
     1.5     1.5
   108.9   118.9
     1.5     1.5
  108.76  118.76
BR Coef= 1 , 1 , 1 ,1.05, 0 ,,,0.8,0,1.2,0,
WSPro=,,,, 1 ,,,, 0 ,,,, 0 ,,,,-1 ,-1 ,-1 , 0 , 0 , 0 , 0 , 0
BC Design=,, 0 ,, 0 ,,,,,,
BC HTab HWMax=126.1
BC Use User HTab Curves=0
BC User HTab FreeFlow(D)= 0

Type RM Length L Ch R = 1 ,2545    ,183.7,103,53.6
BEGIN DESCRIPTION:
K142-00-00-S1_JONES RD - DS - XS2
END DESCRIPTION:
XS GIS Cut Line= 5
       3048609.8      13923564.9      3048628.89     13923238.88
      3048585.52     13922838.65      3048415.73     13922206.45
      3047801.04     13921727.85
#Sta/Elev= 30
2942.625  125.323006.264  125.723205.527  123.223240.882  121.923391.072  121.22
3419.356  120.123448.348  120.973463.409  117.833473.379  113.763514.674  108.51
3529.382   99.913533.483   99.183541.403   99.933543.383  101.433563.465  106.28
3589.202  108.713657.581  111.083672.359  117.843688.976  121.243779.981  120.32
3836.549  123.623893.118  125.223956.758  125.223985.042  123.424013.326  124.62
4034.539  123.22 4098.18  124.824154.748  121.524197.174  123.624392.546  125.92
#Mann= 3 ,-1 , 0
2942.625      .1       03448.348    .055       03688.976      .1       0
#XS Ineff= 2 , 0
       03443.631  120.943693.692       0  120.78
Permanent Ineff=
       F       F
Bank Sta=3448.348,3688.976
XS Rating Curve= 0 ,0
Skew Angle= 45
Exp/Cntr=0.5,0.3

Type RM Length L Ch R = 1 ,2442    ,561.8,672,647.6
BEGIN DESCRIPTION:
K142-00-00-S1_JONES RD - DS - XS1
END DESCRIPTION:
XS GIS Cut Line= 5
       3048813.6      13923446.1      3048618.65      13922502.9
      3048498.99       13922465.      3048484.94      13922082.6
      3047827.08      13921630.1
#Sta/Elev= 30
  3953.4  124.51  4173.4  125.28  4233.4  121.88  4413.4  120.44  4483.4  119.44
  4543.4  121.49  4603.4  117.64  4753.4   115.9  4803.4  119.11  4853.4  117.41
  4903.4  114.64  4926.5  115.55  4956.5  109.31  4968.6  109.54  5001.3    98.7
  5017.2  108.82    5082  109.48    5132  114.82    5212  115.13    5332  121.87
    5382  127.56  5424.6  128.46  5524.6  128.59  5584.6  124.51  5714.6   125.6
  5884.6  122.96  5984.6  124.53  6034.6  121.73  6104.6  125.37  6223.1  126.54
#Mann= 4 ,-1 , 0
  3953.4     .99       0  4413.4     .06       0  4853.4     .04       0
  5424.6     .99       0
#XS Ineff= 2 , 0
       0    4800  120.94    5151       0  120.78
Permanent Ineff=
       F       F
Bank Sta=4968.6,5017.2
XS Rating Curve= 0 ,0
Exp/Cntr=0.3,0.1

Type RM Length L Ch R = 1 ,1770    ,0,0,0
BEGIN DESCRIPTION:
Cross Section K142-00-00-X1
END DESCRIPTION:
XS GIS Cut Line= 4
      3049176.83     13923215.13      3048988.28     13922176.84
      3048971.19     13921943.34       3048098.9     13921692.61
#Sta/Elev= 30
  3800.1   121.7  4160.1   122.2  4520.1   118.2  4530.1   118.3  4550.1   120.9
  4590.1   122.6  4600.1   119.1  4610.1   117.1  4620.1   116.2  4898.6  114.52
  4928.8  107.96  4968.6  107.72  4995.5   98.38  4996.9   97.05  5001.3   96.88
  5004.6    98.2  5017.2     107  5049.9  110.33  5068.7  117.38  5104.2   119.9
  5219.5   124.7  5329.5     125  5499.5   124.1  5629.5   126.2  5699.5   126.1
  5739.5   124.1  5779.5   125.1  5809.5   123.6  5839.5   124.9  5997.1   124.4
#Mann= 4 ,-1 , 0
  3800.1     .07       0  4898.6    .055       0  5068.7      .1       0
  5997.1     .99       0
Bank Sta=4898.6,5068.7
XS Rating Curve= 0 ,0
Exp/Cntr=0.3,0.1
LCMann Table=0

Chan Stop Cuts=-1
Use User Specified Reach Order=0
Composite Channel Slope=5